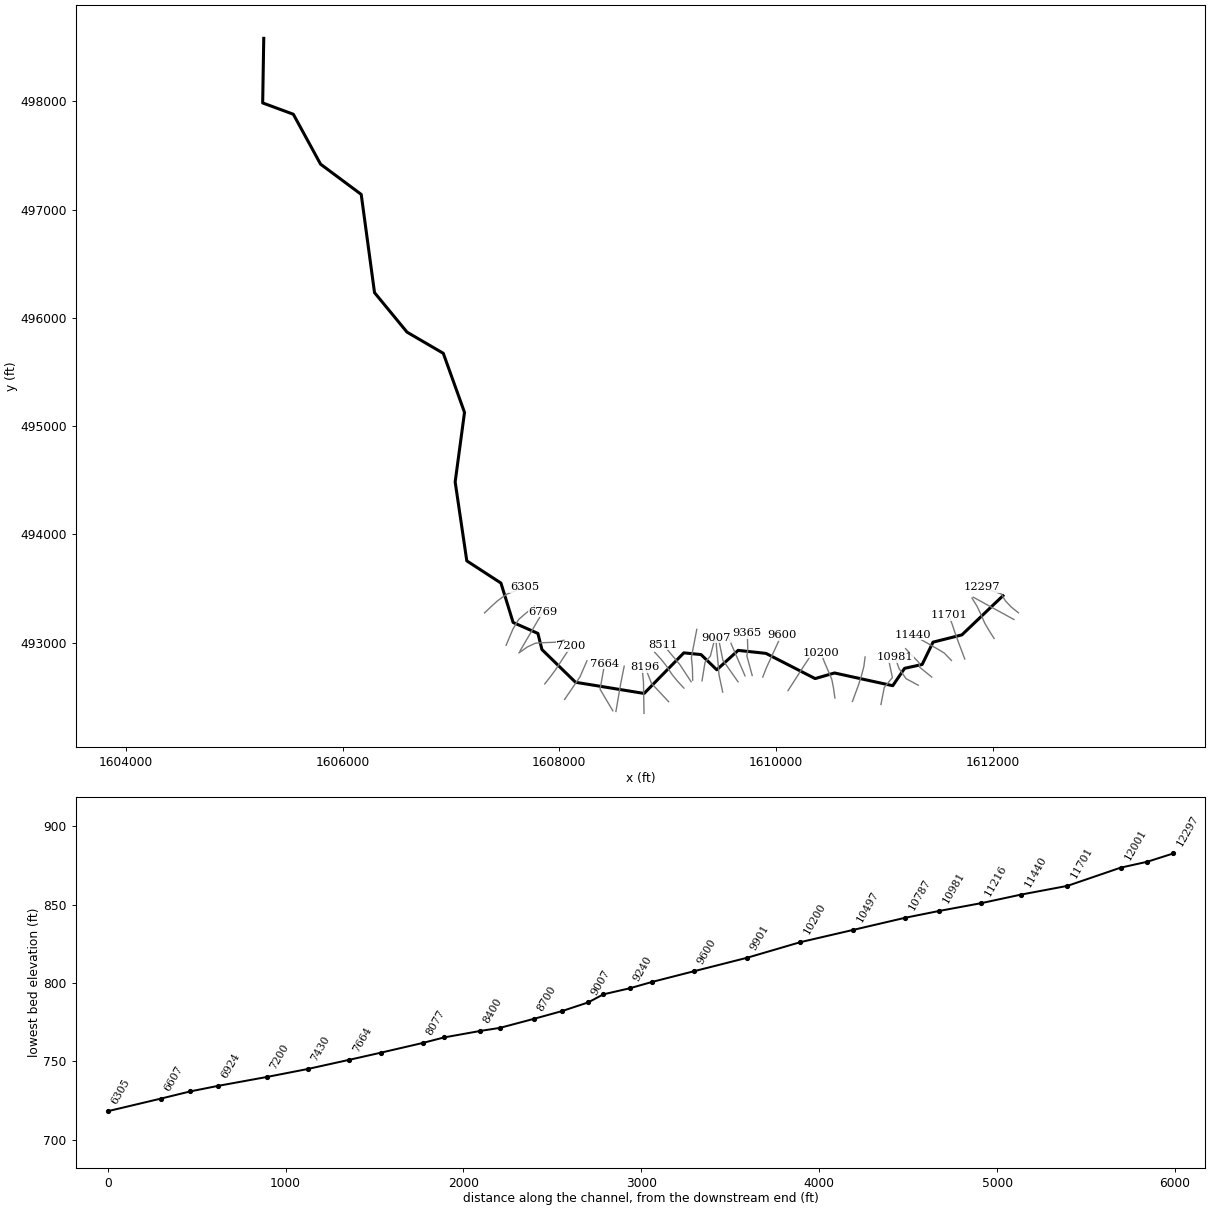
--- HogRn.prj (project) ---

Proj Title=HogRn
Current Plan=p01
Default Exp/Contr=0,0
English Units
Geom File=g01
Flow File=f01
Plan File=p01
BEGIN DESCRIPTION:
---------- MODELED AS PART OF WVEM CTP PROGRAM, 2025----------
Stream Name: Hog Run
Flood Zone: AFH
Marshall County, WV
HEC-RAS Version: RAS 6.6
Vertical Datum: NAVD88
Projection: NAD 1983 StatePlane West Virginia N FIPS 4701 (US Feet)
Terrain: 1-meter West Virginia FEMA R3 South Central (collected 2018-2019)
Land Use: 2024 NLCD
Hydrologic Method:
Duda et al., "Estimation of magnitude and frequency of floods for rural, unregulated streams in and near Virginia and West Virginia." September 8, 2025.
Additional Model Notes:
None
END DESCRIPTION:
DSS Export Rating Curves= 0
DSS Export Rating Curve Sorted= 0
DSS Export Volume Flow Curves= 0
DXF OffsetX= 0
DXF OffsetY= 0
DXF ScaleX= 0
DXF ScaleY= 0

--- HogRn.p01 (plan) ---

Plan Title=Floodplain
Program Version=6.60
Short Identifier=Floodplain
Geom File=g01
Flow File=f01
Subcritical Flow
K Sum by GR= 0
Std Step Tol= 0.01
Critical Tol= 0.01
Num of Std Step Trials= 20
Max Error Tol= 0.3
Flow Tol Ratio= 0.001
Split Flow NTrial= 30
Split Flow Tol= 0.02
Split Flow Ratio= 0.02
Log Output Level= 0
Friction Slope Method= 1
Unsteady Friction Slope Method= 2
Unsteady Bridges Friction Slope Method= 1
Parabolic Critical Depth
Global Vel Dist= 0 , 0 , 0
Global Log Level= 0
CheckData=False
Encroach Param=-1 ,0,0, 0
Flow Ratio Tolerance=0.1
Flow Ratio Min Ratio=0.5
Flow Ratio Max Ratio=4
Flow Ratio Max Iterations= 10
Mapping Interval=1HOUR
Computation Time Step Use Courant=        0
Computation Time Step Use Time Series=    0
Computation Time Step Count To Double=0
Computation Time Step Max Doubling=0
Computation Time Step Max Halving=0
Computation Time Step Residence Courant=0
Run HTab= 0
Run UNet= 0
Run Sediment= 0
Run PostProcess= 0
Run WQNet= 0
Run RASMapper=-1
UNET Theta= 0
UNET Theta Warmup= 0
UNET ZTol= 0
UNET ZSATol= 0
UNET MxIter= 0
UNET Max Iter WO Improvement= 0
UNET MaxInSteps= 0
UNET DtIC= 0
UNET DtMin= 0
UNET MaxCRTS= 0
UNET WFStab= 0
UNET SFStab= 0
UNET WFX= 1
UNET SFX= 1
UNET Gravity=32.17405
UNET 1D Methodology=Finite Difference
UNET DSS MLevel= 1
UNET Pardiso=0
UNET DZMax Abort= 0
UNET Use Existing IB Tables= 0
UNET Froude Reduction=False
UNET Froude Limit= 0
UNET Froude Power= 0
UNET D1 Cores= 0
UNET WindReference=Eulerian
UNET WindDragFormulation=Hsu (1988)
UNET D2 Coriolis=0
UNET D2 Cores= 0
UNET D2 Theta= 1
UNET D2 Theta Warmup= 1
UNET D2 Z Tol= 0.01
UNET D2 Volume Tol= 0.01
UNET D2 Max Iterations= 20
UNET D2 Advanced Convergence=0
UNET D2 WS Max Tol=0.15
UNET D2 WS RMS Tol=0.002
UNET D2 WS Stall Tol=1
UNET D2 Equation= 0
UNET D2 RampUpFraction=0.1
UNET D2 TimeSlices= 1
UNET D2 Turbulence Formulation=Non-Conservative (original)
UNET D2 Eddy Viscosity=0.3
UNET D2 Transverse Eddy Viscosity=0.1
UNET D2 Smagorinsky Mixing=0
UNET D2 BCVolumeCheck=0
UNET D2 Cores=0
UNET D2 SolverType=PARDISO (Direct)
UNET D2 Minimum Iterations= 3
UNET D2 Maximum Iterations= 30
UNET D2 Restart Number= 10
UNET D2 Relaxation Coeff=1.3
UNET D2 SOR Precondition Iterations= 10
UNET D2 ILUT Maximum Fill= 8
UNET D2 ILUT Tolerance=1E-08
UNET D2 Convergence Tolerance=0.00001
PS Theta= 1
PS WS Tol= 0.01
PS Volume Tol= 0.01
PS Max Iterations= 20
PS Equation= 0
PS Advance Time Step=-1
PS Target Courant=0.9
PS Time Slices= 1
PS Iterate With 2D=0
PS Project Initial WSE from DS=-1
PS Ramp Up Initial WSE from US=-1
PS Cores=0
UNET D1D2 MaxIter= 0
UNET D1D2 ZTol=0.01
UNET D1D2 QTol=0.1
UNET D1D2 MinQTol=1
Write IC File= 0
Write IC File at Fixed DateTime=0
Write IC File at Sim End=0
Echo Input=False
Echo Parameters=False
Echo Output=False
Write Detailed= 0
HDF Write Warmup=0
HDF Write Time Slices=0
HDF Flush=0
HDF Compression= 1
HDF Chunk Size= 1
HDF Spatial Parts= 1
HDF Use Max Rows=0
HDF Fixed Rows= 1
Calibration Method= 0
Calibration Iterations= 20
Calibration Max Change=0.05
Calibration Tolerance=0.2
Calibration Maximum=1.5
Calibration Minimum=0.5
Calibration Optimization Method= 1
WQ AD Non Conservative
WQ ULTIMATE=-1
WQ Max Comp Step=1HOUR
WQ Output Interval=15MIN
WQ Output Selected Increments= 0
WQ Create Restart=0
WQ Fixed Restart=0
WQ System Summary=0
WQ Write To DSS=0
Sorting and Armoring Iterations= 10
XS Update Threshold= 0.02
Bed Roughness Predictor= 0
Processes Affected by Predictor=Sediment Only
Hydraulics Update Threshold= 0.02
Energy Slope Method= 1
Volume Change Method= 1
Sediment Retention Method= 0
Sediment TS Multiplier= 1
Warm Up Method= 0
XS Weighting Method= 0
Number of US Weighted Cross Sections= 1
Number of DS Weighted Cross Sections= 1
Upstream XS Weight=0
Main XS Weight=1
Downstream XS Weight=0
Number of DS XS's Weighted with US Boundary= 1
Upstream Boundary Weight= 1
Weight of XSs Associated with US Boundary= 0
Number of US XS's Weighted with DS Boundary= 1
Downstream Boundary Weight= 0.5
Weight of XSs Associated with DS Boundary= 0.5
Percentile Method= 0
Sediment Output Level= 3
Mass or Volume Output= 0
Output Increment Type= 1
Profile and TS Output Increment= 1
Transport Output Increment 1
XS Output Flag= 0
XS Output Increment= 10
Read HDF5 Sediment Hotstart= 0
Sediment Hotstart Type= 0
Write Gradation File= 0
Read Gradation Hotstart= 0
Write HDF5 File= 1
Write Binary Output= 1
Write DSS Sediment File= 0
DSS Sediment Output Type= 1
SV Curve= 0
Specific Gage Flag= 0
Subcell Erosion Methods= 0
Subcell Deposition Methods= 0
Advection Scheme= 1
Matrix Solver= 0
Implicit Weighting Factor= 1
Maximum Outer Loop Convergence Iterations= 5
Convergence Maximum Absolute= 0.001
Convergence RMSE= 0.0001
Grain Fractions Max Abs Error= 0.001
Max Subgrid Regions= 1
Max Subgrid Length Scale= 3.402823E+38
Initial Layer Thickness= 3
Min Layer Thickness= 0.1
Max Layer Thickness= 6
Number of Layers= 5

--- HogRn.f01 (steady flow) ---

Flow Title=Flow
Program Version=6.60
Number of Profiles= 1
Profile Names=P100yr
River Rch & RM=HogRn,Main,12297
     830
River Rch & RM=HogRn,Main,8700
     966
River Rch & RM=HogRn,Main,6305
    1050
River Rch & RM=HogRn,Main,3900
    1350
Boundary for River Rch & Prof#=HogRn,Main            , 1
Up Type= 0
Dn Type= 3
Dn Slope=0.006582
DSS Import GetInterval= 0
DSS Import GetPeak= 0
DSS Import FillOption= 0

--- HogRn.g01 (geometry) ---

Geom Title=Geometry
Program Version=6.60

River Reach=HogRn           ,Main
Reach XY= 30
     1612096.288      493434.085     1611716.947      493072.236
     1611450.891       493005.26     1611350.418      492799.104
     1611188.112      492763.298     1611078.864       492602.93
     1610541.204      492720.493     1610362.437      492668.641
     1609908.427      492901.537     1609651.271      492929.263
     1609454.418      492749.739     1609308.858      492890.447
     1609150.128      492906.389     1608783.455      492531.398
     1608149.921      492634.676     1607840.086      492936.887
     1607802.656      493085.913     1607573.919      493187.112
      1607461.63      493551.013     1607146.249      493756.183
     1607038.899      494485.587     1607125.224      495127.761
     1606929.295       495673.65     1606594.139      495869.374
     1606294.329      496234.295     1606171.495      497141.724
     1605796.059      497421.234     1605544.947      497882.119
     1605261.752      497986.674     1605271.683      498583.438

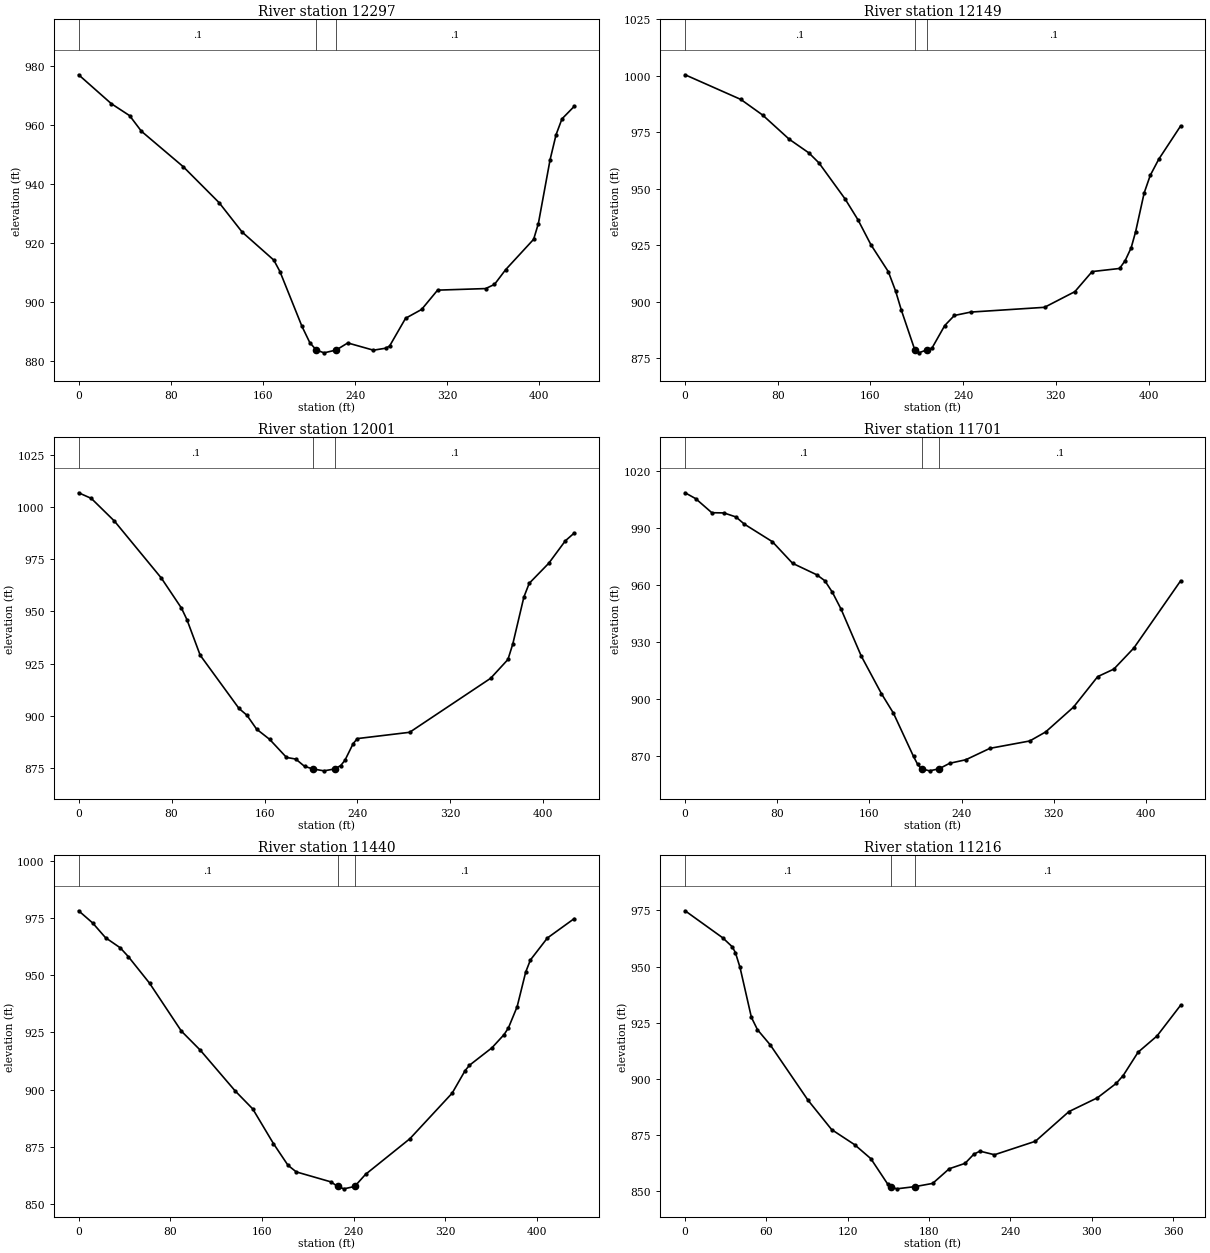
Type RM Length L Ch R = 1 ,12297   ,141.7,147.4,150.8
XS GIS Cut Line= 5
1612238.95747675493276.4884822521612169.61017451493332.551362261
1612118.00332233493388.4784157571612081.41705165493450.046398774
1611898.94682065493514.164380774
#Sta/Elev= 30
       0  977.03    28.4  967.23    44.3  963.17    54.5   957.9    90.8  945.89
     122  933.68     142  923.72   169.5  914.21   174.8  910.35   193.9  891.79
   200.8   886.2206.4099883.7432   213.1  882.79223.6098883.7402   233.7  886.14
     256  883.69   266.5  884.35     270  885.08   283.9   894.5   297.8  897.49
   311.7  904.04   353.4  904.57   361.1  905.98   370.8  910.98   395.1  921.27
   399.2  926.59   409.4  948.28   414.6  956.75   419.7  962.08   430.3  966.31
#Mann= 3 ,-1,0
       0      .1       0206.4099    .045       0223.6098      .1       0
Bank Sta=206.4099,223.6098
XS Rating Curve= 0 ,0
Exp/Cntr(USF)=0,0
Exp/Cntr=0.3,0.1

Type RM Length L Ch R = 1 ,12149   ,152.4,148.7,143.5
XS GIS Cut Line= 2
1612197.41229596493214.5678373831611822.48687223493420.444953004
#Sta/Elev= 30
       0 1000.47    48.1  989.56    66.9  982.66    89.9  971.94   106.8  965.92
   115.5   961.5     138   945.6   149.2  936.32   160.4  925.26   175.4  913.36
   181.7  904.78   186.6  896.41  198.21  878.83   201.6  877.45   209.1  878.83
   213.1  879.56   224.1  889.53   232.4  893.98   246.5  895.48   310.2  897.59
   336.4  904.52   351.3   913.4     375  914.78   379.8  918.23     385  923.93
   388.8  930.93   396.2  948.15   401.5     956   408.8   963.1   427.7  977.84
#Mann= 3 ,-1,0
       0      .1       0  198.21    .045       0   209.1      .1       0
Bank Sta=198.21,209.1
XS Rating Curve= 0 ,0
Exp/Cntr(USF)=0,0
Exp/Cntr=0.3,0.1

Type RM Length L Ch R = 1 ,12001   ,298.9,300,298.8
XS GIS Cut Line= 6
1612014.57472342 493039.138563261611967.60696959493113.461577341
1611929.27076018493178.3485866791611888.90240259493269.844466671
1611856.65509176493337.6218901721611810.18471226493412.545296758
#Sta/Elev= 30
       0 1006.75    10.9 1004.06    30.8  993.21    71.2  965.93    88.5  951.57
    93.2  946.07   104.6  929.05     138  903.57   144.8  900.34   153.2  893.65
   164.4  888.77   178.9  880.13   186.9  879.34   194.4  875.87  201.66874.6076
   211.2  873.71  220.28874.6072   225.6  876.25   229.2  878.76   236.3  886.75
   239.9  889.14   284.9  892.15   354.6  917.99   369.5  926.99   373.7  934.46
   383.2  956.83   387.8  963.43   404.6  973.01   418.9  983.77   426.5  987.46
#Mann= 3 ,-1,0
       0      .1       0  201.66    .045       0  220.28      .1       0
Bank Sta=201.66,220.28
XS Rating Curve= 0 ,0
Exp/Cntr(USF)=0,0
Exp/Cntr=0.3,0.1

Type RM Length L Ch R = 1 ,11701   ,252.9,260.5,263.2
XS GIS Cut Line= 6
1611743.75144617492849.4548875091611712.94507734492931.302820921
1611686.53961834493001.4581924231611652.30543484493095.568240419
1611628.51184726493167.6638967541611596.34327643 493253.55250451
#Sta/Elev= 30
       0 1008.51     9.2 1005.42    23.2  998.01    33.7   997.9    44.2  995.77
    51.4  992.01    75.8  982.74    93.3  971.37   114.3  965.32   121.3   962.2
   127.9  956.07   135.4  947.24   152.9  922.56   170.4  902.77   180.9   892.4
   198.3  869.65   201.9  865.46  205.28 863.133   212.2  862.06  220.45863.1324
   229.7  866.04   243.7   867.9   264.6   873.9   299.2  877.79     313  882.54
   337.2  895.63   358.2  911.69   372.2  915.64   389.6  926.76   430.2  962.15
#Mann= 3 ,-1,0
       0      .1       0  205.28    .045       0  220.45      .1       0
Bank Sta=205.28,220.45
XS Rating Curve= 0 ,0
Exp/Cntr(USF)=0,0
Exp/Cntr=0.3,0.1

Type RM Length L Ch R = 1 ,11440   ,231.7,223.7,215.2
XS GIS Cut Line= 6
1611620.35303192492836.1033420661611554.35382008492904.607470149
1611490.10132392492943.3327864051611403.27603826492992.944891909
1611338.15740208493030.1544631511611262.18544117493073.565793658
#Sta/Elev= 30
       0   978.3    12.2  972.98    23.5   966.5    36.3  962.09    43.3  958.27
    61.9  946.59    89.7  925.59   106.3  917.18   136.7  899.36     152   891.5
   170.1  876.29   182.8  866.79     190  863.91   220.3  859.53  226.11857.5369
   231.6  856.49  240.96857.5351   250.5  862.85   289.2  878.45   326.1  898.42
   337.4  908.29   341.2  910.63   360.8  918.27   371.4  924.06   375.2     927
   382.8  936.26   390.3  951.48   394.4  956.75   409.2  966.37   432.6  974.85
#Mann= 3 ,-1,0
       0      .1       0  226.11    .045       0  240.96      .1       0
Bank Sta=226.11,240.96
XS Rating Curve= 0 ,0
Exp/Cntr(USF)=0,0
Exp/Cntr=0.3,0.1

Type RM Length L Ch R = 1 ,11216   ,225.8,235.2,233.9
XS GIS Cut Line= 4
1611438.60494344492683.0550373911611326.93206611492773.789250227
1611321.50352346492815.6665792291611197.42254864492945.176096696
#Sta/Elev= 30
       0  974.86    27.8   962.8    34.8  958.81    37.1  956.24    40.5  949.65
    48.9   927.4    53.4  921.88    62.8  915.14    90.7  890.47   108.1  877.41
     125  870.71     137  864.47   149.4  853.18  151.62852.0272     156  851.03
  169.68852.0257   182.6  853.45   194.8  859.97   206.5  862.38     213  866.48
   217.5  867.81   228.2  866.21   258.4  872.22   283.1  885.43   304.1  891.57
   317.9  897.95   323.1  901.46   334.1  911.87   348.1  919.12   365.5  932.81
#Mann= 3 ,-1,0
       0      .1       0  151.62    .045       0  169.68      .1       0
Bank Sta=151.62,169.68
XS Rating Curve= 0 ,0
Exp/Cntr(USF)=0,0
Exp/Cntr=0.3,0.1

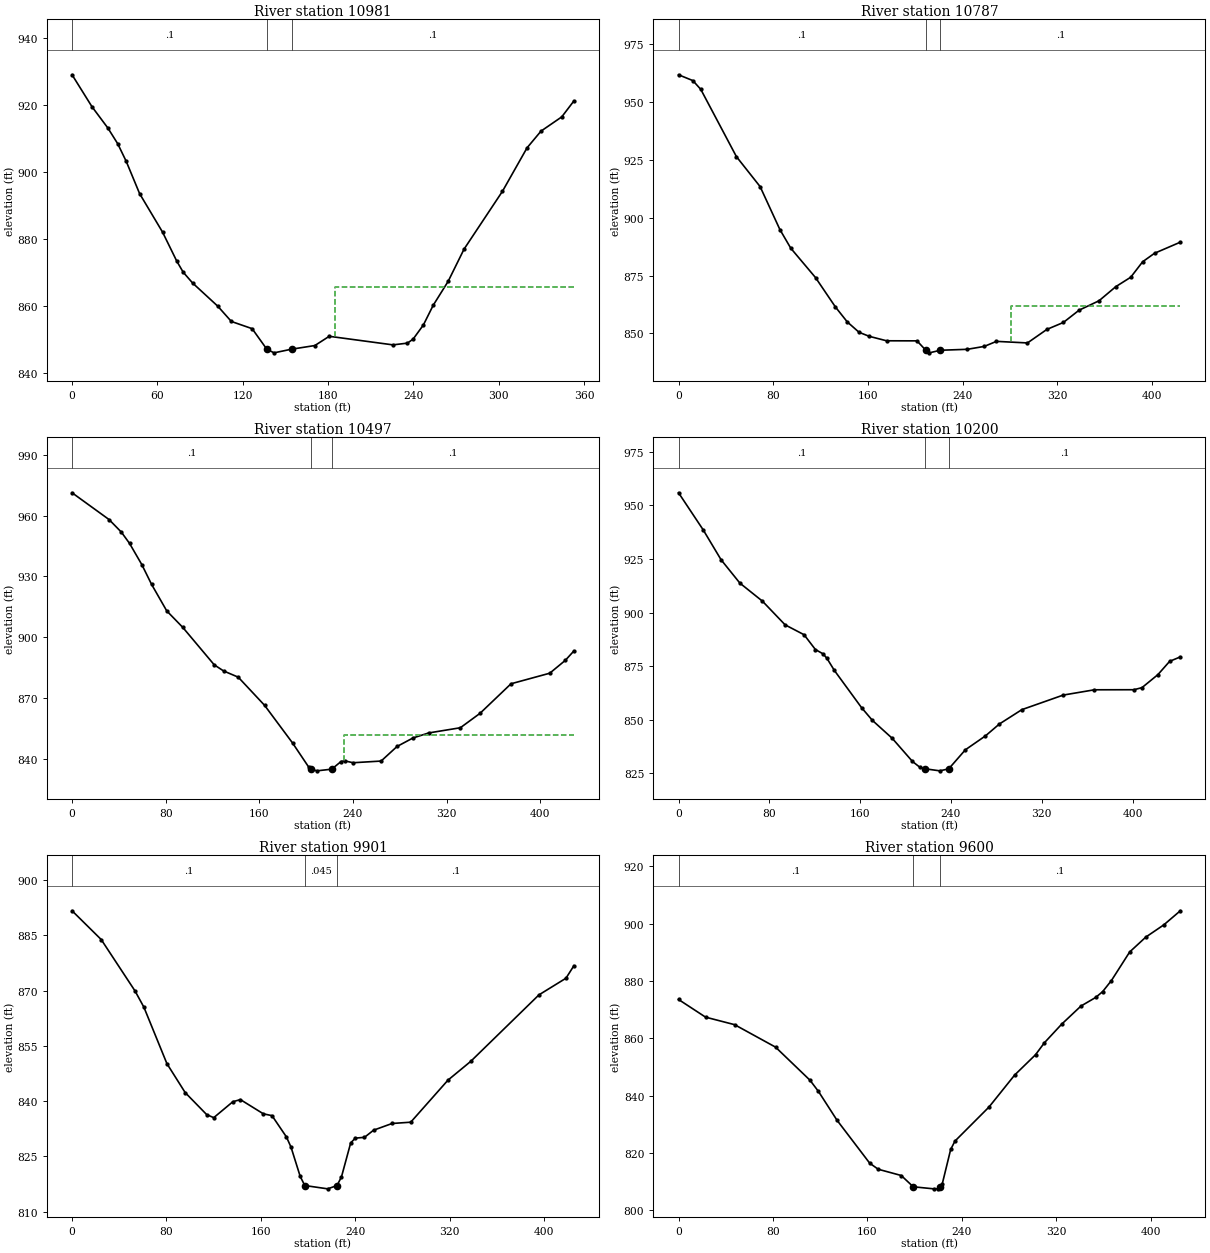
Type RM Length L Ch R = 1 ,10981   ,199.8,194.6,182.6
XS GIS Cut Line= 4
1611314.52396862492607.0554403141611202.07558519492667.544915539
1611136.93307341492761.3811527451611100.48428706492866.074475249
#Sta/Elev= 30
       0  929.13      14  919.59    25.2  913.21    32.1  908.53    38.1  903.25
    47.5  893.62    63.6  882.15    73.6  873.48    78.1  870.18    84.8  866.91
   102.4  860.03     112  855.45   126.6   853.3  136.92847.1688     142  846.08
  154.28 847.168   170.7  848.26   180.8  851.02   225.6  848.46   235.8  848.98
   239.8  850.19     247   854.4   253.9  860.28   264.4  867.42   275.6  877.06
   302.6  894.33   319.9  907.32   329.7   912.3   344.3  916.56   352.8   921.3
#Mann= 3 ,-1,0
       0      .1       0  136.92    .045       0  154.28      .1       0
#XS Ineff= 2 , 0
                          184.96          865.89
Permanent Ineff=
       F       F
Bank Sta=136.92,154.28
XS Rating Curve= 0 ,0
Exp/Cntr(USF)=0,0
Exp/Cntr=0.3,0.1

Type RM Length L Ch R = 1 ,10787   ,287.2,289.2,289
XS GIS Cut Line= 4
1610969.75213318492429.5076511281611000.85627842492587.561710507
1611075.62374833492678.0683257091611045.70629469492820.307040211
#Sta/Elev= 30
       0  961.59    12.1  959.08    18.8  955.29    48.9  926.27    68.9  913.35
    85.6  894.83    94.8  886.77   115.7   874.1   132.5  861.43   142.5  854.99
   152.5  850.49   161.1  848.76   175.7  846.84   201.4  846.81  208.85842.7589
   211.8  841.64  221.15842.7565   243.8  843.16   258.2  844.41   268.5  846.59
   294.7  845.91   311.1  851.75     325  854.74   338.3  860.04   355.1  864.09
   369.3  870.19   381.9  874.25     392  880.94     402  884.59   423.8  889.38
#Mann= 3 ,-1,0
       0      .1       0  208.85    .045       0  221.15      .1       0
#XS Ineff= 2 , 0
                          280.67          861.68
Permanent Ineff=
       F       F
Bank Sta=208.85,221.15
XS Rating Curve= 0 ,0
Exp/Cntr(USF)=0,0
Exp/Cntr=0.3,0.1

Type RM Length L Ch R = 1 ,10497   ,288.3,297.2,302.7
XS GIS Cut Line= 6
1610706.59013468492457.6298837511610736.89814493492539.713381007
1610762.87611134492610.0705237541610792.75137967492705.928271666
1610812.01544876492779.3080461771610823.64206593492868.598878086
#Sta/Elev= 30
       0   971.3    31.6  958.08    42.1  951.88    49.1  946.31    59.6  935.83
    67.9  926.11    80.9  912.97    94.6  904.82   121.5  886.31   129.5   883.3
     142  880.23   164.5  866.33   188.4  847.74   202.3  835.75  204.38834.7957
   209.2  833.97  221.87834.7941   229.8  838.55   232.9  838.92   240.1  837.97
   264.1   838.8   277.7     846   291.3   850.2   304.8  852.69   331.8  855.25
   348.6  862.36   375.1  876.97   408.2  882.19   421.5  888.54   428.8  893.16
#Mann= 3 ,-1,0
       0      .1       0  204.38    .045       0  221.87      .1       0
#XS Ineff= 2 , 0
                          232.62          851.47
Permanent Ineff=
       F       F
Bank Sta=204.38,221.87
XS Rating Curve= 0 ,0
Exp/Cntr(USF)=0,0
Exp/Cntr=0.3,0.1

Type RM Length L Ch R = 1 ,10200   ,311,299.4,288.4
XS GIS Cut Line= 6
1610544.75121951492489.4936651741610531.70039259492581.977732167
1610515.72503084 492662.83419776    1610474.9738492758.147327334
1610445.62116842492827.1675305071610415.55593984492909.466906592
#Sta/Elev= 30
       0  955.86    21.7  938.58    37.5   924.6    54.1  913.69    73.9  905.31
    93.9  894.25   110.6  889.64   120.6  882.73   127.3  880.73   130.7  878.66
   137.3  872.98   161.2  855.65   170.8  849.68   188.3   841.3   206.1  830.52
   212.7  827.77  217.41827.0765   230.2  826.14  238.06827.0776   252.7  835.95
   270.4  842.44   282.7     848   302.5  854.69   338.9  861.48   366.4  863.95
   401.2  863.98   408.3  864.95   422.3     871   432.7  877.23   442.1  879.29
#Mann= 3 ,-1,0
       0      .1       0  217.41    .045       0  238.06      .1       0
Bank Sta=217.41,238.06
XS Rating Curve= 0 ,0
Exp/Cntr(USF)=0,0
Exp/Cntr=0.3,0.1

Type RM Length L Ch R = 1 ,9901    ,298.5,300.8,302.1
XS GIS Cut Line= 6
1610111.96632393492557.4777811771610159.24050759492631.095744178
1610199.76273626492694.2019171711610253.57890159492778.500633091
1610295.34259759492840.8600884231610340.41665442 492916.31334959
#Sta/Elev= 30
       0   891.7    24.7  883.89    53.4  869.91    60.9  865.51    80.4  850.19
    95.9  842.32   114.1  836.35   120.1  835.51   136.3  839.84   142.7  840.42
   162.2  836.55   169.5  836.06   181.7  830.29   185.6  827.52   193.4  819.56
  197.28817.0818   216.7  816.18  224.62817.0775   228.4  819.44   236.2  828.65
   240.1  829.95   247.9  830.17   255.6  832.11   271.3  833.93   287.1  834.28
   318.7  845.71   337.9  850.78   395.8  868.86   418.7  873.38   425.4  876.76
#Mann= 3 ,-1,0
       0      .1       0  197.28    .045       0  224.62      .1       0
Bank Sta=197.28,224.62
XS Rating Curve= 0 ,0
Exp/Cntr(USF)=0,0
Exp/Cntr=0.3,0.1

Type RM Length L Ch R = 1 ,9600    ,229.8,234.8,236.6
XS GIS Cut Line= 6
1609878.68037318492682.4804839191609910.25511317492764.269690424
1609941.59822634492832.4063651711609983.38915326492923.255264834
 1610014.7325945492991.391939595 1610051.2994505493070.884890839
#Sta/Elev= 30
       0  873.52    22.9  867.36    47.5  864.74    82.2  856.91   111.4  845.37
   118.6  841.45   134.3  831.42     162  816.45   169.2  814.34   188.7  812.16
  198.88808.2291   216.2  807.51   219.8  807.54   221.3808.2304   223.4  809.11
   230.6  821.23   234.2  824.14   263.1  836.04   284.8  847.17   302.5  854.26
     310  858.42   324.7  864.93     341  871.23   353.4  874.21   359.4  876.27
   366.8  880.11   382.3  890.09     396  895.28   411.2  899.53   425.2  904.44
#Mann= 3 ,-1,0
       0      .1       0  198.88    .045       0   221.3      .1       0
Bank Sta=198.88,221.3
XS Rating Curve= 0 ,0
Exp/Cntr(USF)=0,0
Exp/Cntr=0.3,0.1

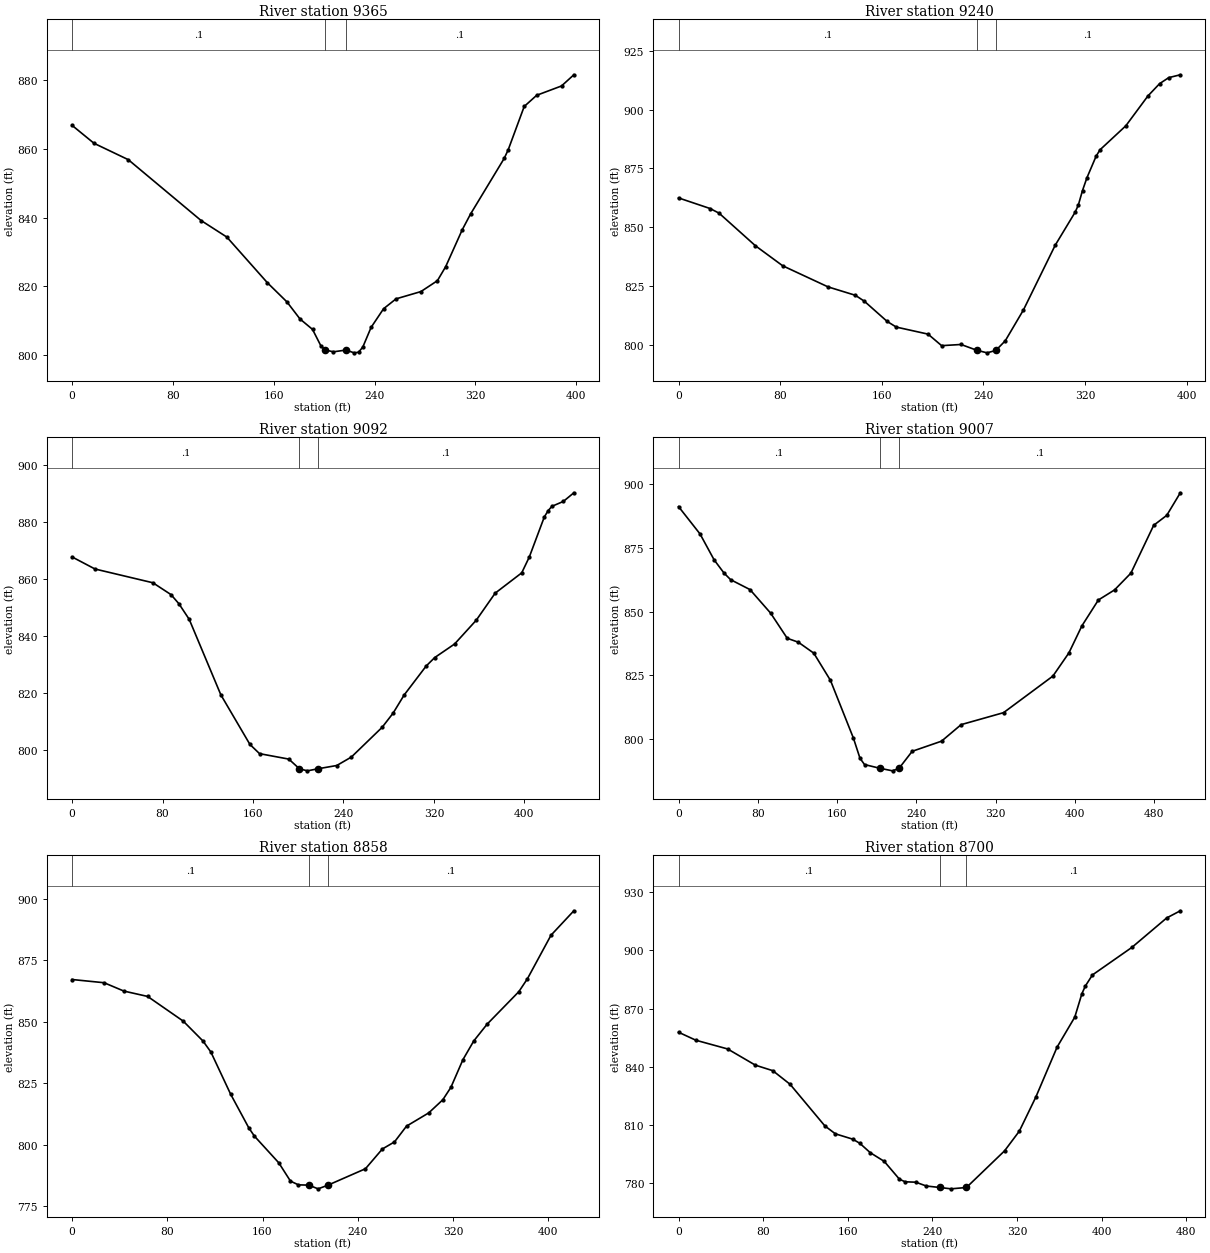
Type RM Length L Ch R = 1 ,9365    ,120.1,125.6,128.5
XS GIS Cut Line= 4
1609781.28519257492696.8460566031609731.86774068492878.258644225
1609740.76141696492934.0139863031609735.99123444493087.649404577
#Sta/Elev= 30
       0  866.81    17.4   861.6    44.6  856.84   102.4  839.15   122.8  834.35
     155  821.07   170.5  815.51   180.9  810.53   190.8  807.52   197.4  802.77
   200.8  801.53   207.4     801   217.4  801.51   223.8   800.7   227.3  800.87
   230.7  802.36   237.3   808.1   247.2  813.52   257.1  816.39   276.8   818.5
   289.9  821.66   296.5  825.76   309.6  836.45   316.2  841.03   342.9   857.2
   346.1  859.71   358.8   872.3   368.7  875.55   388.4  878.26   398.2  881.51
#Mann= 3 ,-1,0
       0      .1       0   200.8    .045       0   217.4      .1       0
Bank Sta=200.8,217.4
XS Rating Curve= 0 ,0
Exp/Cntr(USF)=0,0
Exp/Cntr=0.3,0.1

Type RM Length L Ch R = 1 ,9240    ,144.1,147.8,146.6
XS GIS Cut Line= 2
1609714.97699062 492694.230313521609557.93700687493056.678596027
#Sta/Elev= 30
       0  862.45    24.8  857.95    31.9  855.98    60.5  842.14      82  833.62
   117.7  824.66   139.2  821.09   146.3  818.56   164.2     810   171.4  807.59
   196.4   804.6   207.1   799.7   222.4   800.2   234.8  797.74   242.9  796.65
   249.8  797.68   257.2  801.77   271.5  814.87   296.5  842.35   312.2  856.38
   314.7   859.4     318   865.6   321.5  871.03   328.7  880.16   331.8   882.9
   352.1  893.08   369.5  905.76   378.7  910.99   385.9  913.54     395  914.75
#Mann= 3 ,-1,0
       0      .1       0   234.8    .045       0   249.8      .1       0
Bank Sta=234.8,249.8
XS Rating Curve= 0 ,0
Exp/Cntr(USF)=0,0
Exp/Cntr=0.3,0.1

Type RM Length L Ch R = 1 ,9092    ,91,85.3,79.7
XS GIS Cut Line= 3
1609650.47645364492638.7510884681609510.88535697492837.668401224
1609471.10189442493034.491847531
#Sta/Elev= 30
       0  867.71    20.3  863.48    71.5  858.66    87.5  854.51    94.5  851.31
   103.6  845.86   131.6   819.4   157.3  802.04   165.8  798.81   191.7   796.9
   201.1   793.5   208.2  792.79   217.4793.5088   234.1  794.66     247  797.61
   274.2  808.02   283.9  812.98   293.7  819.35   313.2  829.51   320.7  832.45
   338.3  837.21   357.5  845.56   374.2  855.02   397.7  862.14   404.4  867.69
   417.7  881.74   421.1  883.94   424.4  885.44   434.5  887.15   443.8  890.18
#Mann= 3 ,-1,0
       0      .1       0   201.1    .045       0   217.4      .1       0
Bank Sta=201.1,217.4
XS Rating Curve= 0 ,0
Exp/Cntr(USF)=0,0
Exp/Cntr=0.3,0.1

Type RM Length L Ch R = 1 ,9007    ,155.5,148.7,139.6
XS GIS Cut Line= 6
1609508.87271383492544.0834510031609490.53941718492629.641022667
1609474.82520975 492702.976505921609465.48041217492818.072076261
1609454.25044775492929.298559844 1609445.4486281493045.550952002
#Sta/Elev= 30
       0  891.15    21.7  880.43    35.9  870.29    45.9  865.11    52.6  862.51
    72.1  858.64    92.9  849.43   109.7  839.56   120.9  838.02   136.5  833.73
   153.3  823.08   176.5  800.44   183.1  792.58   187.7  790.09   202.9  788.66
     216  787.63   222.6  788.65   235.8  795.28   265.4  799.25   285.2  805.73
     328  810.42   377.8  824.75     394  833.86   407.1  844.45   423.7  854.56
     440   858.5   456.5  865.07   479.5  883.81   492.7  887.72   506.4  896.56
#Mann= 3 ,-1,0
       0      .1       0   202.9    .045       0   222.6      .1       0
Bank Sta=202.9,222.6
XS Rating Curve= 0 ,0
Exp/Cntr(USF)=0,0
Exp/Cntr=0.3,0.1

Type RM Length L Ch R = 1 ,8858    ,151.8,157.9,162.5
XS GIS Cut Line= 4
1609317.97991169492647.7464783281609345.61894883492819.234140589
 1609395.2435837492877.0248546111609437.33029934493043.487237392
#Sta/Elev= 30
       0  867.25    26.9  865.94    43.5  862.55    63.5  860.36    93.4  850.31
     110  842.21   116.6  837.75   133.2   820.6   148.5  806.85   153.2   803.5
   173.7  792.62   183.5  785.18   190.2  783.66   198.9  783.55   206.7  782.04
  214.94 783.524   246.5  790.22   260.7  798.26   270.9  801.15     281  807.56
   299.7  812.97   311.5   818.3   318.3  823.36   328.4  834.62   337.5  842.24
   348.7  849.06   375.4  862.32   382.6  867.57   402.4  885.28   421.6  895.23
#Mann= 3 ,-1,0
       0      .1       0   198.9    .045       0  214.94      .1       0
Bank Sta=198.9,214.94
XS Rating Curve= 0 ,0
Exp/Cntr(USF)=0,0
Exp/Cntr=0.3,0.1

Type RM Length L Ch R = 1 ,8700    ,174.1,189.1,197
XS GIS Cut Line= 6
1609231.87195551492654.1130865961609229.06126559492771.085293591
1609219.85557534492865.6218499241609238.85684967492963.799803168
1609253.10813351493037.4335141781609269.73474067493123.339182258
#Sta/Elev= 30
       0  857.85    16.4  853.72    46.4  849.23    72.7  840.86    89.1  838.03
   105.5     831   138.4  809.53   148.3  805.47   164.8   802.7   171.4  800.58
   181.3  795.74   194.5  791.27   208.9  782.06   214.3  780.73   224.3  780.53
   234.3  778.56  247.04   777.8   257.7   777.1  272.26777.7994   308.3  796.69
   322.3  806.88   337.9  824.46     358  850.21   374.7  865.64   381.4  877.69
   384.7  881.69   391.4  887.39   428.7  901.59   461.6  916.77   474.5  920.47
#Mann= 3 ,-1,0
       0      .1       0  247.04    .045       0  272.26      .1       0
Bank Sta=247.04,272.26
XS Rating Curve= 0 ,0
Exp/Cntr(USF)=0,0
Exp/Cntr=0.3,0.1

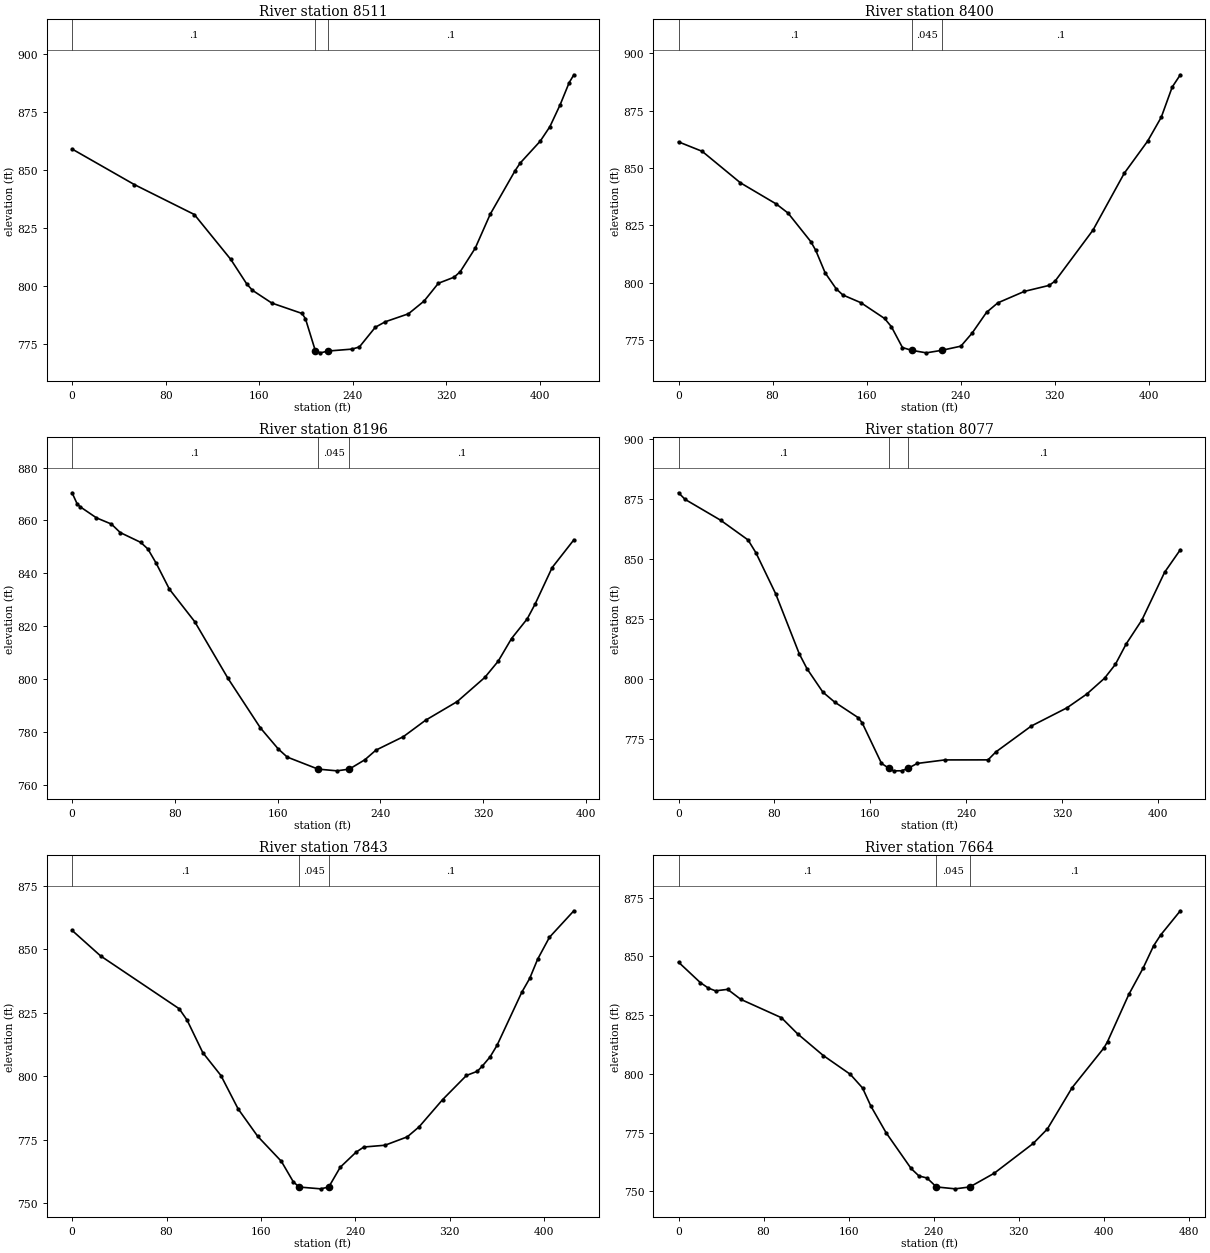
Type RM Length L Ch R = 1 ,8511    ,112.6,110.9,109
XS GIS Cut Line= 3
1609217.31673204492639.6540000421609113.89465877492796.765127743
1608959.86044764492981.917361326
#Sta/Elev= 30
       0  859.22    53.3  843.88   104.5     831   135.7  811.62   149.4     801
   154.2  798.33   170.7  792.85   196.6  788.35   199.5  786.07     208  772.18
   212.3  771.39  218.89  772.17   239.4     773   245.6  773.94   259.2  782.42
   267.8   784.8   287.5  788.21   300.9  793.71   313.1  801.37   326.6     804
   331.8  806.38   344.6   816.5   357.4  831.12   378.7  849.91     383  853.16
   400.1  862.57   408.4  868.84   417.2  878.32   424.9  887.84   428.9  891.21
#Mann= 3 ,-1,0
       0      .1       0     208    .045       0  218.89      .1       0
Bank Sta=208,218.89
XS Rating Curve= 0 ,0
Exp/Cntr(USF)=0,0
Exp/Cntr=0.3,0.1

Type RM Length L Ch R = 1 ,8400    ,200.8,203.8,205.2
XS GIS Cut Line= 6
1609150.58930968492580.8589680051609090.73673908492645.645255759
1609043.07640134492703.9968450961608987.60669601492787.202059254
1608941.10186775 492846.227859841608881.51963784492910.983635843
#Sta/Elev= 30
       0  861.39    20.1  857.27    52.6  843.55    83.1  834.31    93.1  830.36
   112.5  817.89   116.7  814.08   124.7  804.26   134.1  797.31   139.7  794.65
   155.1  791.27   175.2   784.4     181  780.82   190.4  771.73  198.22770.5134
   210.7  769.42  223.77770.5129   240.1  772.33   249.6  777.99   261.9  787.07
   271.5  791.21   294.1  796.21   315.2  798.83   320.3  800.76   352.4   822.9
     379  847.69   398.9  861.71   410.5  872.14   419.8   885.3   426.7  890.64
#Mann= 3 ,-1,0
       0      .1       0  198.22    .045       0  223.77      .1       0
Bank Sta=198.22,223.77
XS Rating Curve= 0 ,0
Exp/Cntr(USF)=0,0
Exp/Cntr=0.3,0.1

Type RM Length L Ch R = 1 ,8196    ,125.1,119.1,113.3
XS GIS Cut Line= 3
1609009.88581967492454.912777534 1608851.0241721 492624.51595999
1608793.92443401492772.070728726
#Sta/Elev= 30
       0  870.45     3.9  866.31     6.2  865.19      19  860.96    30.6  858.62
    37.5   855.4    53.4   851.7      59   849.2    65.4  843.86    75.8  833.96
    95.5  821.68   121.4  800.22   146.6  781.51   160.5  773.55   167.5  770.47
  191.48765.9243   206.2  765.27  215.78765.9234   227.9  769.45   236.5  773.09
   257.9   778.2   275.2  784.42   299.8  791.47   321.3  800.61   331.7  806.74
   342.1  815.32   354.3  822.76   360.4  828.32   373.7  842.16   390.6  852.65
#Mann= 3 ,-1,0
       0      .1       0  191.48    .045       0  215.78      .1       0
Bank Sta=191.48,215.78
XS Rating Curve= 0 ,0
Exp/Cntr(USF)=0,0
Exp/Cntr=0.3,0.1

Type RM Length L Ch R = 1 ,8077    ,234.3,234.2,232.1
XS GIS Cut Line= 3
1608782.45437814492347.2572058521608777.43255957492639.383515609
 1608764.8423355492765.158278968
#Sta/Elev= 30
       0  877.59     5.5  874.83    35.1  866.16      58  857.94    64.6  852.56
      81  835.56   100.7  810.53   107.2  804.27   120.4  794.55   130.2  790.41
   149.9  783.91   153.2  781.75   169.3  764.88  175.59762.7847   179.4  761.76
     186  761.78  191.37762.7877   199.1  764.84   222.1  766.31   258.2  766.33
   264.7  769.63   294.3  780.43     324     788   340.5  793.72   355.4  800.35
   364.4  806.09   373.4   814.6   386.6  824.64   405.5  844.48   418.6  853.87
#Mann= 3 ,-1,0
       0      .1       0  175.59    .045       0  191.37      .1       0
Bank Sta=175.59,191.37
XS Rating Curve= 0 ,0
Exp/Cntr(USF)=0,0
Exp/Cntr=0.3,0.1

Type RM Length L Ch R = 1 ,7843    ,178.9,179,178.8
XS GIS Cut Line= 6
1608523.10988337 492365.03632951 1608537.8355757492451.288453596
 1608550.4575977492525.2187519251608567.65736646492623.729053589
1608582.15897787492697.3384864211608599.51917936492783.140808257
#Sta/Elev= 30
       0  857.36    24.2  847.29    90.7  826.52    97.4  822.06   110.7  809.25
   126.1  800.21   140.7  787.04   157.3  776.24   177.3  766.42   187.3  758.45
  192.21756.2971   210.6  755.58  217.45 756.297   227.2  764.09   240.6  770.02
   247.2  772.05   265.1  772.75     284  776.06     294     780     314  790.76
   334.1  800.23   343.3  801.87   347.5   803.9   354.2  807.59     360  812.07
     381  833.01   387.7  838.45   394.4  845.99   404.4  854.63   425.1  865.08
#Mann= 3 ,-1,0
       0      .1       0  192.21    .045       0  217.45      .1       0
Bank Sta=192.21,217.45
XS Rating Curve= 0 ,0
Exp/Cntr(USF)=0,0
Exp/Cntr=0.3,0.1

Type RM Length L Ch R = 1 ,7664    ,235.4,234.1,230.4
XS GIS Cut Line= 3
1608494.47753573492371.2911678021608376.70060517492569.677597663
1608419.06236437492807.278074195
#Sta/Elev= 30
       0  847.58    20.4  838.92    28.1  836.52    34.8  835.37    46.2     836
    58.6  831.73    96.8  823.92     112  817.05   136.2   807.8   161.6   799.8
   173.1  793.99   180.9   786.3   195.2  774.96   218.8  759.67   226.2  756.48
   233.7  755.63  242.62751.8086   260.3     751  274.06751.8073     297  757.65
   333.7  770.34     347  776.49   370.3  794.11   400.3  811.09   403.6  813.72
   423.6  833.81     437  844.97     447  854.59   453.6  859.16   472.1  869.48
#Mann= 3 ,-1,0
       0      .1       0  242.62    .045       0  274.06      .1       0
Bank Sta=242.62,274.06
XS Rating Curve= 0 ,0
Exp/Cntr(USF)=0,0
Exp/Cntr=0.3,0.1

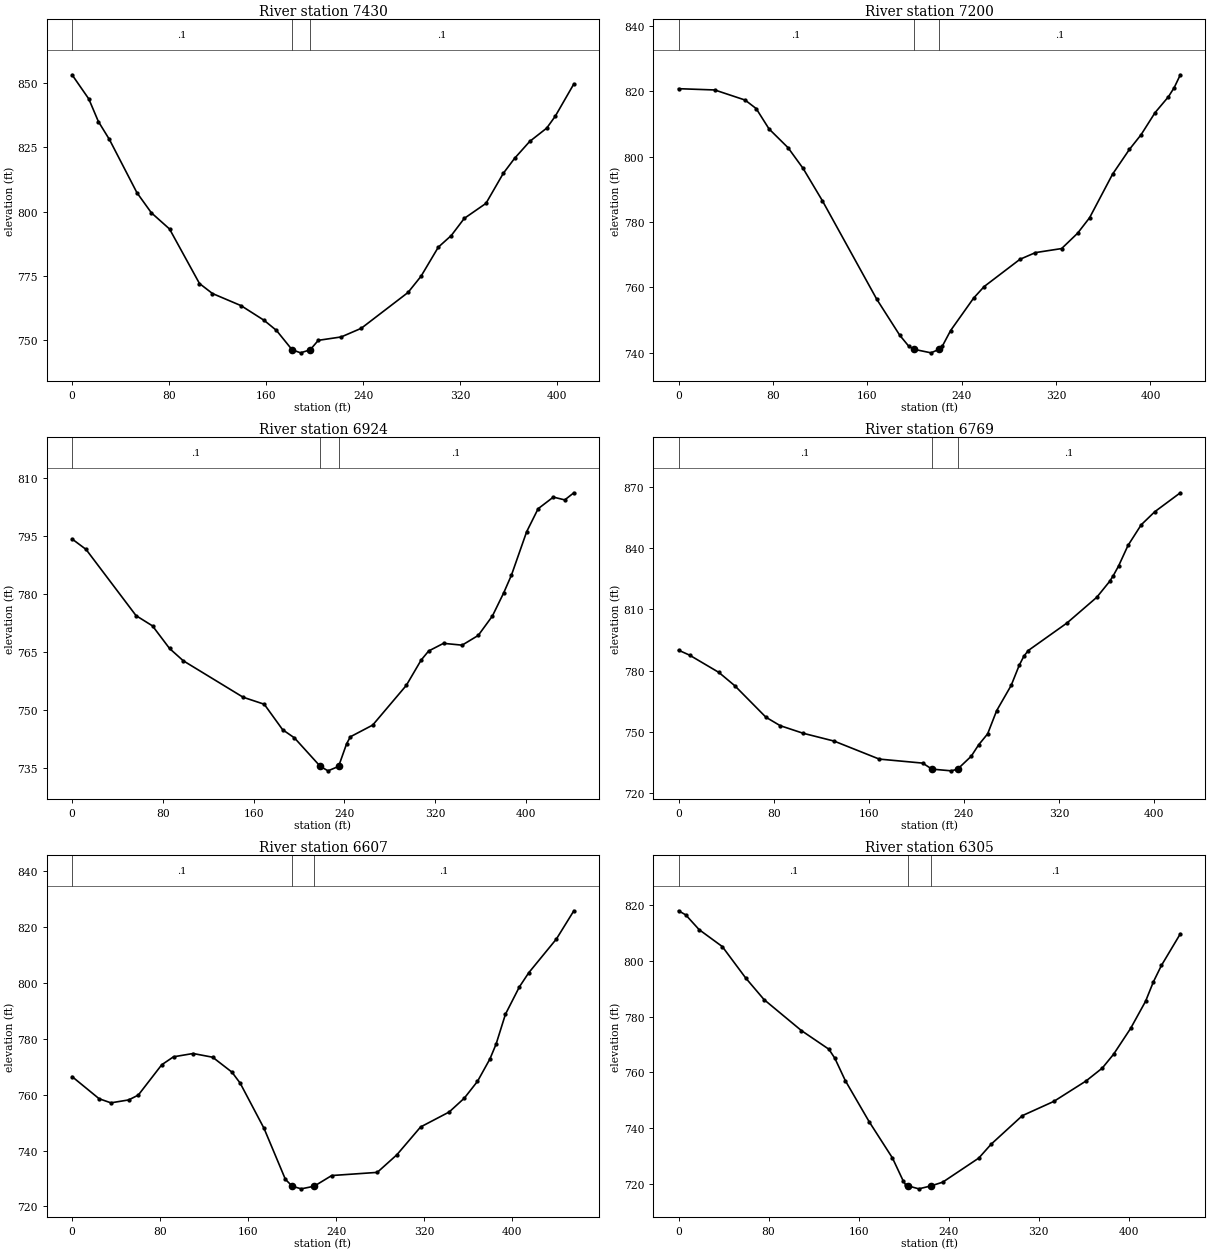
Type RM Length L Ch R = 1 ,7430    ,227.7,229.9,229.6
XS GIS Cut Line= 3
1608049.05661484 492475.921553531608190.95794416492683.968124009
1608255.40715349492832.653580628
#Sta/Elev= 30
       0   853.2    13.8  843.81    21.7  835.02    30.8  828.05    53.5  807.36
    65.4  799.55    80.4  793.25   105.1  772.05   115.8  768.17   139.4  763.45
   158.3  757.78   168.6  753.82  181.48746.3096   188.5  745.11   196.4  746.29
   203.1  749.97     222  751.29   238.5  754.64   277.1  768.57   287.8  774.85
   302.1  786.19   312.8  790.72   323.5  797.37   341.4  803.21   355.7  814.89
     365  820.71   377.5   827.3   391.5  832.46   398.6  837.12   413.9  849.65
#Mann= 3 ,-1,0
       0      .1       0  181.48    .045       0   196.4      .1       0
Bank Sta=181.48,196.4
XS Rating Curve= 0 ,0
Exp/Cntr(USF)=0,0
Exp/Cntr=0.3,0.1

Type RM Length L Ch R = 1 ,7200    ,284.8,276.1,268
XS GIS Cut Line= 6
1607865.89010742492619.3903869991607919.88606243492688.446023166
1607964.75375484492748.7041047511608019.25397393492832.547441006
1608060.51045309492895.1821582621608109.64880626492967.602289006
#Sta/Elev= 30
       0  820.72    30.7  820.33    56.4  817.25    65.8  814.65    76.7  808.43
    92.8   802.7   105.6  796.35     122  786.44     168   756.4   187.5  745.39
     195   742.1  199.17741.1273     214  740.02  221.01741.1281   223.5     742
   230.6  746.83   250.1  756.74     259  760.26   289.4   768.6   302.5  770.64
   324.7  771.88   338.2  776.55   348.4   781.3   367.9  794.62   382.1  802.15
     392  806.64   403.9  813.41   415.2  818.25   420.1  821.04   425.3  824.97
#Mann= 3 ,-1,0
       0      .1       0  199.17    .045       0  221.01      .1       0
Bank Sta=199.17,221.01
XS Rating Curve= 0 ,0
Exp/Cntr(USF)=0,0
Exp/Cntr=0.3,0.1

Type RM Length L Ch R = 1 ,6924    ,144.5,154.7,162.8
XS GIS Cut Line= 6
1607627.45494049492905.9590287421607707.75005548 492962.18726275
1607781.13803207492996.0385730031607881.01676931493001.635346583
1607955.98413906493003.8410508251608042.30516065 493022.78392633
#Sta/Elev= 30
       0  794.22    12.3  791.53    56.4  774.41    70.9  771.76    85.9  765.93
      98  762.75   150.8  753.32   169.4  751.51   185.6  744.93     196  742.82
  218.78735.4578   225.6   734.3  234.92735.4477     242   741.3   245.3   743.1
     265  746.13   294.6  756.38   307.7  762.93   314.3  765.27   327.4  767.25
   343.8  766.78     358  769.29   370.5  774.31   380.5  780.32   387.3  784.89
   400.7   796.1   410.8  802.04   424.2  805.04   434.3  804.32   442.3  806.16
#Mann= 3 ,-1,0
       0      .1       0  218.78    .045       0  234.92      .1       0
Bank Sta=218.78,234.92
XS Rating Curve= 0 ,0
Exp/Cntr(USF)=0,0
Exp/Cntr=0.3,0.1

Type RM Length L Ch R = 1 ,6769    ,162.2,162.2,162.5
XS GIS Cut Line= 2
1607636.86345154492922.1864806371607849.69679029493286.674344168
#Sta/Elev= 30
       0     790     9.3  787.56    33.9   779.1    47.3  772.57    73.5  757.11
    85.5  752.96   104.7  749.25   130.9  745.38   168.8  736.56   205.4  734.58
   213.1731.6361   229.4  730.79  234.72731.6083   246.2  737.95   252.4  743.52
     260  748.93   267.6  760.32   279.8   772.7   286.6  782.61   290.4  786.95
   294.2  789.84   326.7  803.31   351.8  815.95   362.6  823.73   365.7  826.57
   370.2  831.37   378.1  841.41   389.2  851.53   400.6  857.94   422.1  867.24
#Mann= 3 ,-1,0
       0      .1       0   213.1    .045       0  234.72      .1       0
Bank Sta=213.1,234.72
XS Rating Curve= 0 ,0
Exp/Cntr(USF)=0,0
Exp/Cntr=0.3,0.1

Type RM Length L Ch R = 1 ,6607    ,306.3,301.5,298.3
XS GIS Cut Line= 6
1607509.30355026492976.4539773321607543.25820675493057.097188756
1607572.36247925   493126.220082  1607625.121232493215.068657592
1607692.68277667493273.1764810091607770.97002168 493337.16027692
#Sta/Elev= 30
       0  766.46    24.6  758.53    35.3  757.06    51.5  758.11    60.2  759.84
    81.5  770.69    92.2  773.54     110  774.72   127.8  773.39   145.3  768.06
   152.8  764.11   174.5  747.91   193.9  729.68  200.16727.2115   208.3  726.28
     220727.2117     236  731.04   277.4  732.17   295.2  738.46   316.8  748.43
   342.8  753.79   356.5  758.73   368.5  764.75   379.8  772.77   385.4  778.07
   393.9  788.77   406.6  798.58   415.1  803.63   440.3  815.75   456.1  825.81
#Mann= 3 ,-1,0
       0      .1       0  200.16    .045       0     220      .1       0
Bank Sta=200.16,220
XS Rating Curve= 0 ,0
Exp/Cntr(USF)=0,0
Exp/Cntr=0.3,0.1

Type RM Length L Ch R = 1 ,6305    ,299.6,303.8,301.4
XS GIS Cut Line= 6
1607309.82724318493275.1521988361607373.15290393493335.532983586
1607428.64787167493385.9836700861607511.53386076493446.880858004
1607589.73252326 493477.507437171607679.42230451493513.403034672
#Sta/Elev= 30
       0  817.97     6.4   816.5    18.3   811.2    38.9  805.12    59.7  793.83
      76  786.08   109.2  774.96   133.6  768.27   138.9  765.03   148.2     757
   169.3  742.31   190.1  729.22   199.5  721.13   201.8  719.63   204.3 719.178
   213.5  718.15  224.09 719.178   234.7  720.53   266.8  729.19   277.8  734.18
   305.5  744.42   333.5  749.54     362  756.84   376.5  761.48   386.6  766.47
   401.7  775.72     415  785.47     422  792.49   429.1  798.34   445.9   809.7
#Mann= 3 ,-1,0
       0      .1       0   204.3    .045       0  224.09      .1       0
Bank Sta=204.3,224.09
XS Rating Curve= 0 ,0
Exp/Cntr(USF)=0,0
Exp/Cntr=0.3,0.1