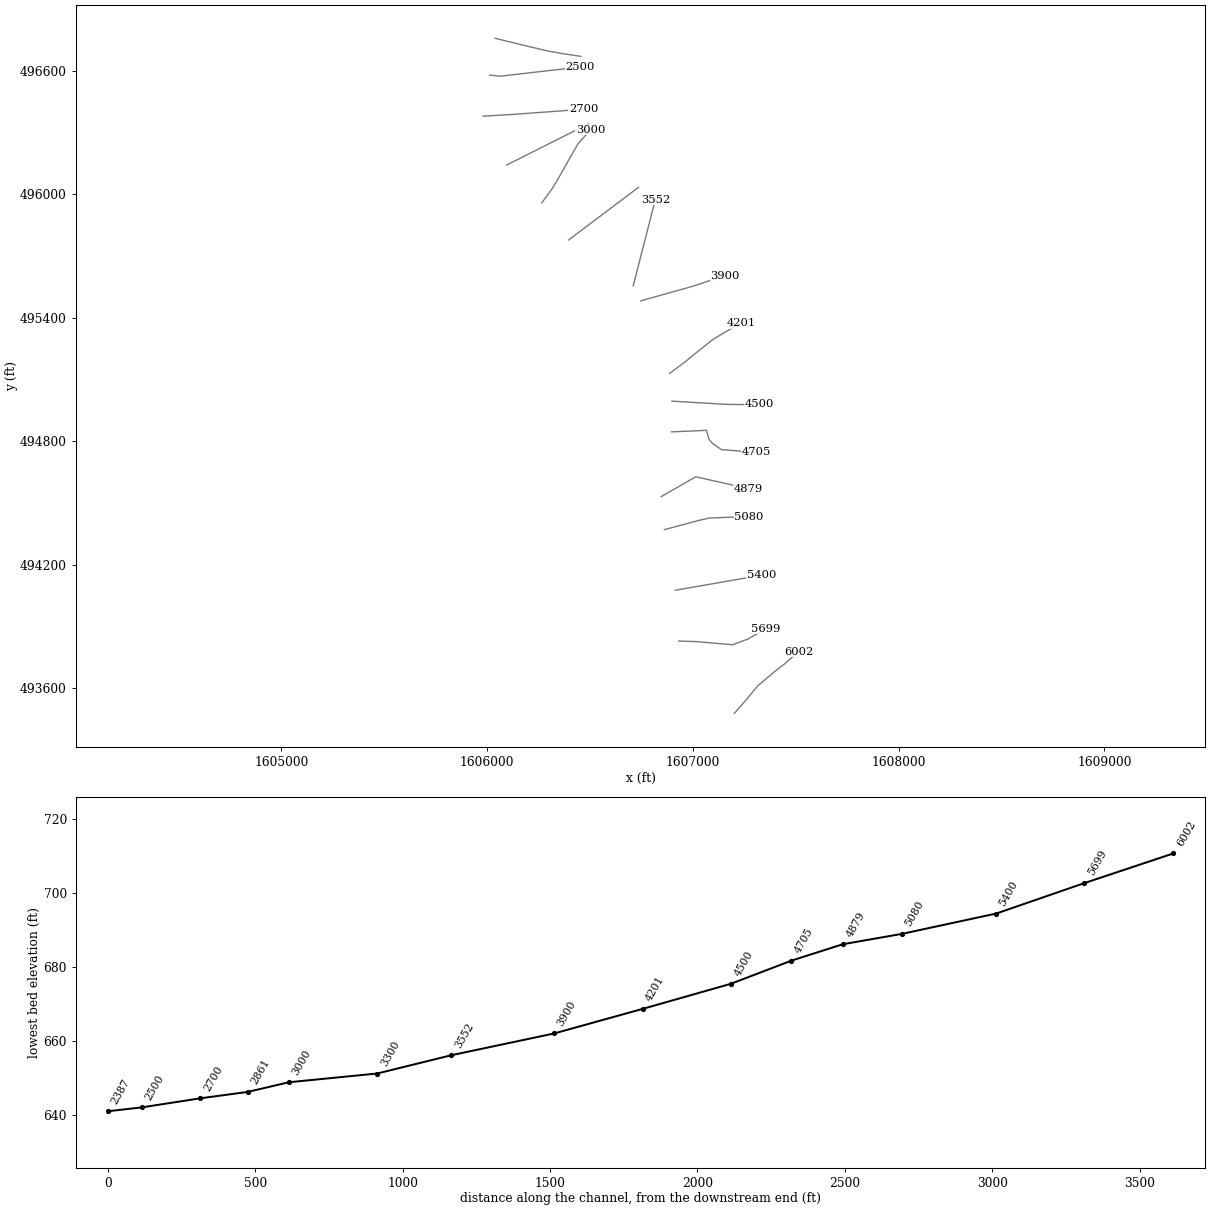
HEC-RAS study HogRn.prj: HogRn

--- HogRn.g01 (geometry) --- (continued)

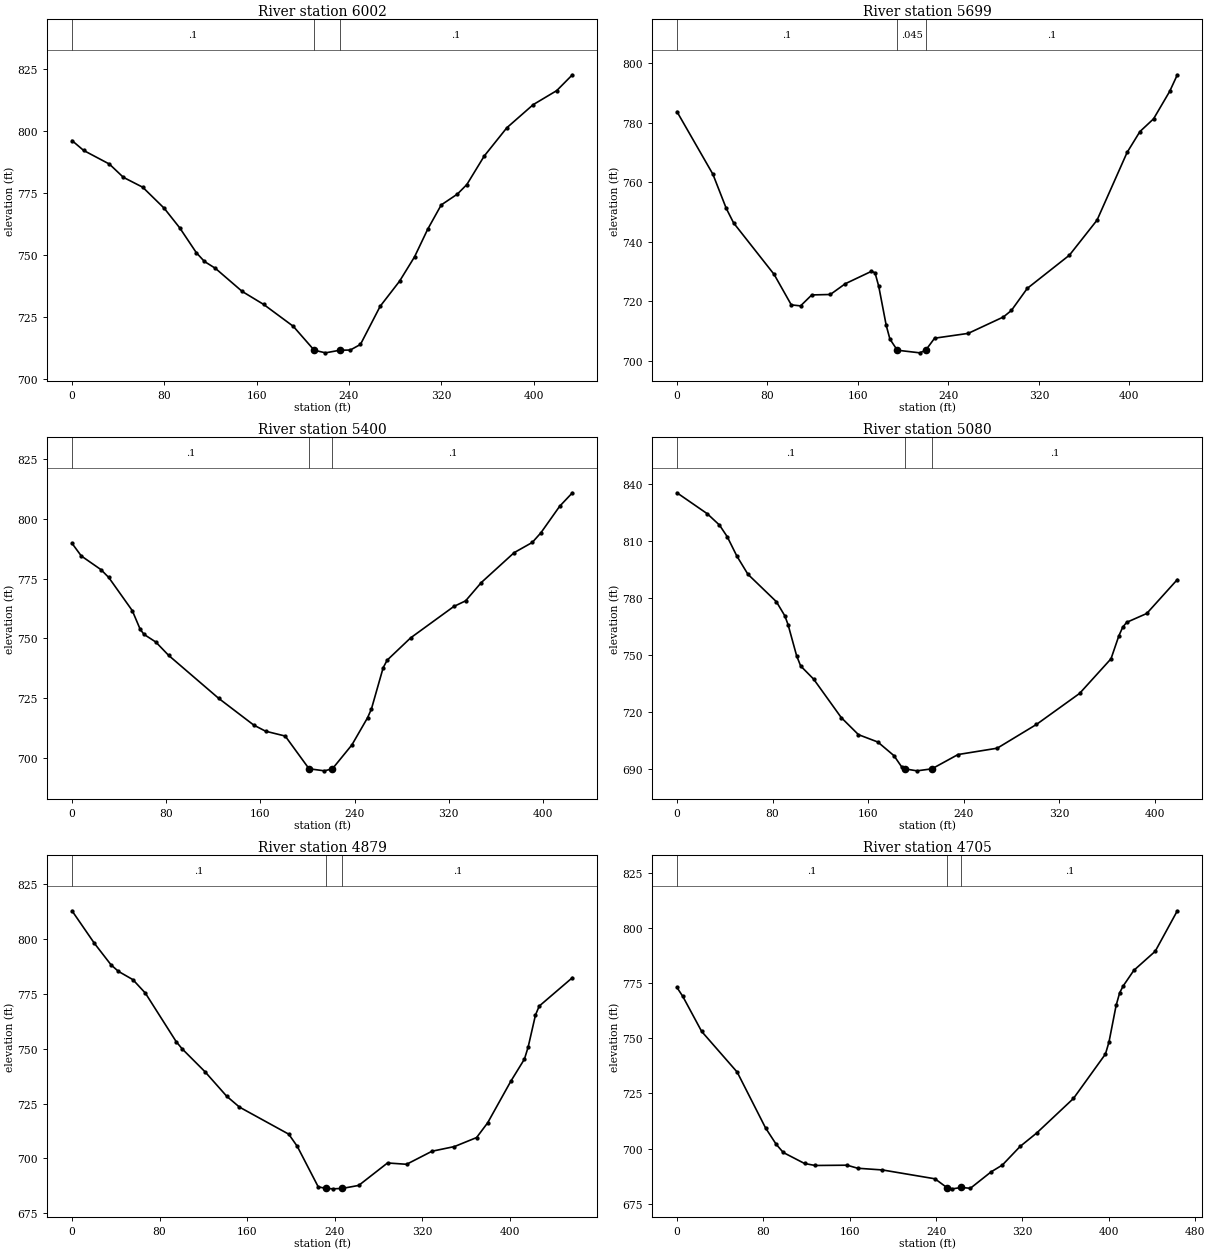
Type RM Length L Ch R = 1 ,6002    ,316.9,302.6,297
XS GIS Cut Line= 6
1607201.36715826493476.7318481651607263.38573501493547.502375916
1607311.64580908493607.1475978341607387.98391101493672.162887752
1607447.02742809493718.4095144271607513.01056384493776.002903178
#Sta/Elev= 30
       0  796.25    10.1  792.26    32.4  786.77    44.5  781.43    61.3  777.43
    79.9  768.96    93.4  761.03   107.8  751.01   114.8  747.49   124.2  744.76
   147.5  735.42   166.2  730.15   191.8  721.35  209.92 711.712   219.7  710.66
  232.15711.7115   241.2  711.79     250  714.05   267.1  729.44   283.9  739.55
   296.9  749.38   308.3  760.51     320  770.29     334  774.66   342.2   778.5
   357.3  790.02   376.9  801.42   399.7  810.72   420.1  816.38   433.7  822.77
#Mann= 3 ,-1,0
       0      .1       0  209.92    .045       0  232.15      .1       0
Bank Sta=209.92,232.15
XS Rating Curve= 0 ,0
Exp/Cntr(USF)=0,0
Exp/Cntr=0.3,0.1

Type RM Length L Ch R = 1 ,5699    ,294.5,298.9,300.6
XS GIS Cut Line= 6
1606931.28961442 493828.237706841607018.92854676493825.499195263
1607093.64755742493818.8594447521607193.30516651493810.301062927
1607268.54550159493838.4657047541607354.49283625493888.365211248
#Sta/Elev= 30
       0  783.71    31.8  762.66    43.6  751.18    50.1   746.3    85.9  729.01
   101.1  718.76   109.3  718.42   119.2   722.1   135.6  722.25   148.8  725.86
   171.9  730.02   175.1  729.57   178.4  725.02     185  711.91   188.3  707.25
  194.83703.5219   214.7  702.64  219.93703.5229   227.8  707.56   257.5  709.18
   288.7  714.71   295.7  716.89   309.7  724.29     347  735.47   371.4  747.23
     398  770.01   409.3  776.99   421.4  781.29   435.6   790.5   442.4  796.09
#Mann= 3 ,-1,0
       0      .1       0  194.83    .045       0  219.93      .1       0
Bank Sta=194.83,219.93
XS Rating Curve= 0 ,0
Exp/Cntr(USF)=0,0
Exp/Cntr=0.3,0.1

Type RM Length L Ch R = 1 ,5400    ,318.7,319.6,319.7
XS GIS Cut Line= 6
1606914.53111775494075.1775016781607000.73698209 494090.16959767
1607074.62823851494103.0199656781607173.14936693 494120.15346159
1607247.04029526494133.0041576771607333.24648768 494147.99592559
#Sta/Elev= 30
       0  789.75     7.9  784.45    24.6  778.72    31.2  775.44    51.2  761.55
    57.9  753.74    61.2  751.58    71.2  748.39    82.1  742.79   124.5  724.83
   154.4  713.59   164.4  711.04   181.1     709  201.32695.3003   214.4  694.43
  221.19   695.3   237.7  705.28     251  716.65   254.3  720.34   264.3  737.66
   267.7  740.81   287.6  750.13   324.3  763.29   334.3  765.65   347.6   773.3
   375.5  785.83   390.9  790.11   398.2  794.13   414.2  805.28     425  810.92
#Mann= 3 ,-1,0
       0      .1       0  201.32    .045       0  221.19      .1       0
Bank Sta=201.32,221.19
XS Rating Curve= 0 ,0
Exp/Cntr(USF)=0,0
Exp/Cntr=0.3,0.1

Type RM Length L Ch R = 1 ,5080    ,205.1,200.9,196.7
XS GIS Cut Line= 4
1606861.68835555494369.7685989091607030.61668041494414.960222777
1607081.49763515494426.2671016081607273.03038465494433.383916924
#Sta/Elev= 30
       0  835.45    25.4   824.4    35.6  818.43    42.1  812.29    50.1  802.15
    59.4  792.51    83.2  778.07    90.3  770.59      93  765.94   100.1  749.67
   103.5  744.22   114.4  737.26   137.5     717   151.9  708.01   168.1  704.13
   181.6  696.94   188.3  690.79  190.73689.9966   200.8  688.95  213.33689.9988
   235.2  697.54     268  700.88   300.8  713.39   336.9  729.73   363.2  747.99
   369.8  760.15     373  764.63   376.3  767.19   393.1  771.85   418.7  789.73
#Mann= 3 ,-1,0
       0      .1       0  190.73    .045       0  213.33      .1       0
Bank Sta=190.73,213.33
XS Rating Curve= 0 ,0
Exp/Cntr(USF)=0,0
Exp/Cntr=0.3,0.1

Type RM Length L Ch R = 1 ,4879    ,175.1,174.1,169.2
XS GIS Cut Line= 5
1606845.50040025494529.7754017771607014.08771563494626.646287641
1607111.64854412494604.6948879731607184.81932954494588.231338224
1607270.18497246494569.024027564
#Sta/Elev= 30
       0   812.9    20.5  798.03    35.7  788.22    42.4  785.28    55.6  781.51
      67  775.36    95.1  753.27   100.6  749.95   121.5   739.5   141.2  728.39
   152.9  723.41   197.9  711.07   205.7  705.51   224.8  687.08   231.5  686.37
   238.3  686.15  246.92686.3512   261.8  687.71   288.1  697.95   305.5  697.34
   328.7  703.29   349.2  705.42   369.4  709.52   379.5  716.23   400.6  735.14
   413.1  745.29   416.5  750.79   423.2  765.41   426.6  769.45   456.9  782.41
#Mann= 3 ,-1,0
       0      .1       0   231.5    .045       0  246.92      .1       0
Bank Sta=231.5,246.92
XS Rating Curve= 0 ,0
Exp/Cntr(USF)=0,0
Exp/Cntr=0.3,0.1

Type RM Length L Ch R = 1 ,4705    ,204.1,205.4,211.4
XS GIS Cut Line= 6
1606896.12763833494844.8100663121607066.35898072494852.347985532
1607078.92217942494807.7486301461607094.62617779 494789.53199203
1607138.59737324494758.7521552141607306.94423583494744.932636643
#Sta/Elev= 30
       0  773.05     5.4  769.01    22.9   753.1    55.8  734.66    82.1  709.33
    91.9  701.95    98.5  698.21   118.2  693.22     128  692.32   157.6  692.45
   167.4  691.07   190.4  690.29     239  686.28  249.95682.3359   255.2  681.73
   263.4  682.34   271.8  681.98   291.1  689.46   301.4  692.51   317.9  700.97
   333.1  706.99   367.3  722.72   396.9  742.84   400.2  748.34   406.8  764.91
   410.1  770.64   413.3  773.69   423.2  780.79     443  789.44   463.5  807.81
#Mann= 3 ,-1,0
       0      .1       0  249.95    .045       0   263.4      .1       0
Bank Sta=249.95,263.4
XS Rating Curve= 0 ,0
Exp/Cntr(USF)=0,0
Exp/Cntr=0.3,0.1

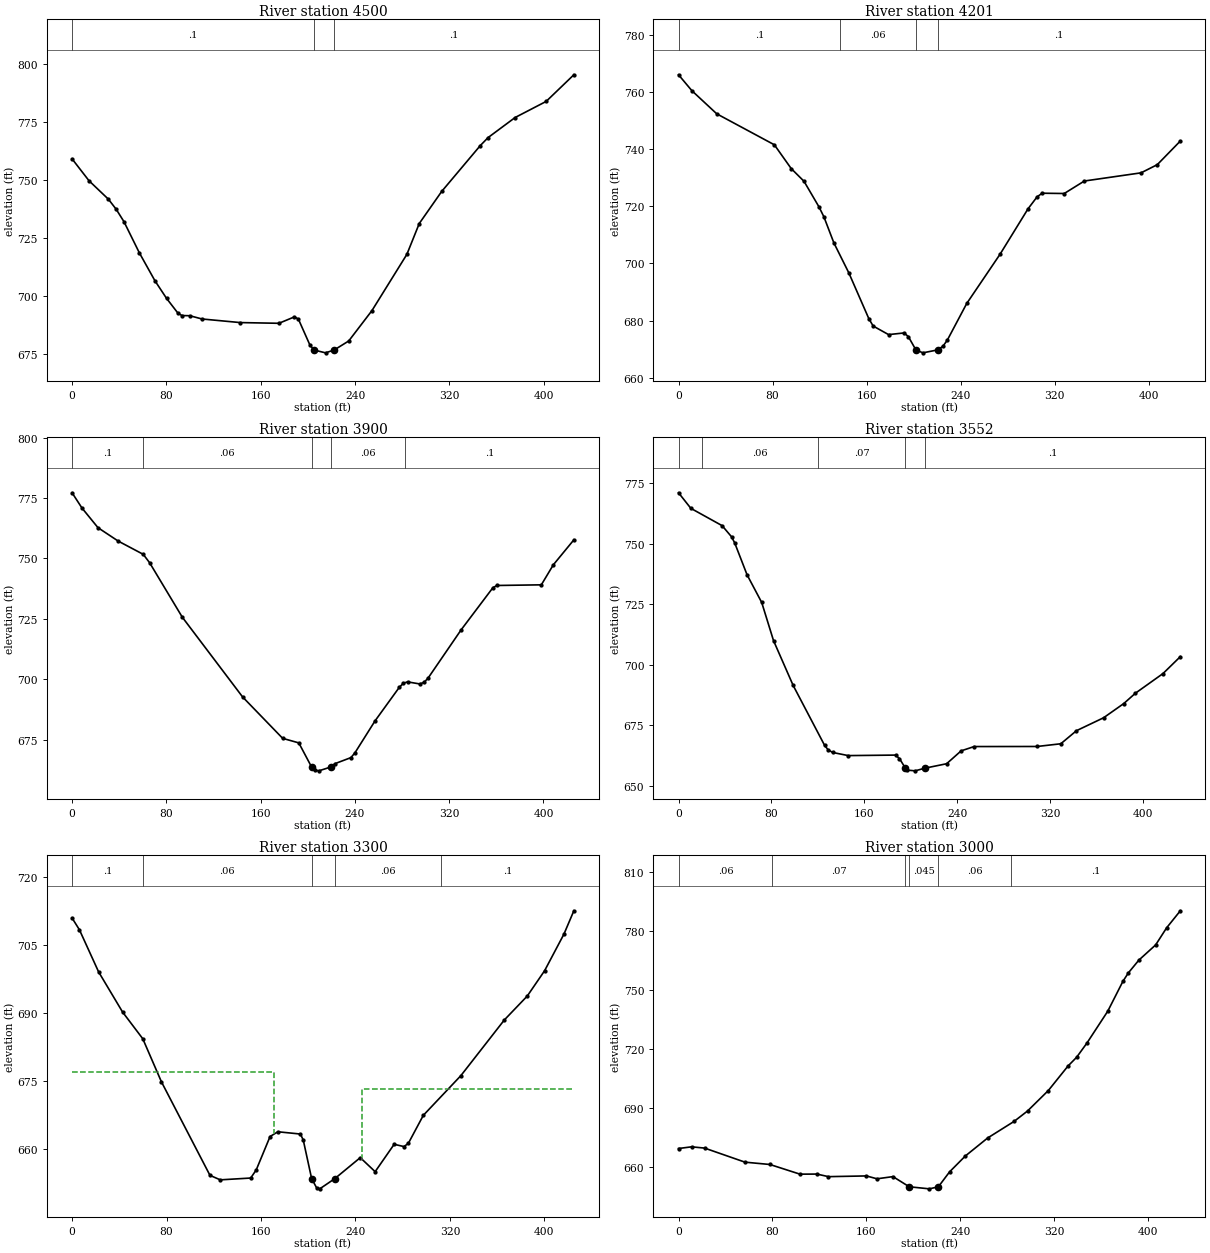
Type RM Length L Ch R = 1 ,4500    ,292.1,299.4,305.3
XS GIS Cut Line= 6
1606898.13580935494994.3695609271606985.47946668 494989.13991259
1607060.34513059494984.6573100091607160.16645326494978.680944011
1607235.22699867494977.4450540841607323.07656051494980.672081754
#Sta/Elev= 30
       0  759.19    14.4  749.73    30.8  741.79    37.4  737.45      44  732.09
    57.1  718.59    70.3  706.56    80.1     699      90  692.46    93.3  691.58
    99.8   691.5   110.2  690.09   142.6  688.54   175.4  688.23   188.6  691.01
   191.9  690.05   201.7  678.83  205.21676.6946   214.9  675.48  222.21676.6939
   234.6   680.6   254.3  693.72   283.9  717.98   294.4  731.29   313.4  745.12
   346.2  764.95   352.8  768.39   375.7  777.04     402  783.98   425.5  795.48
#Mann= 3 ,-1,0
       0      .1       0  205.21    .045       0  222.21      .1       0
Bank Sta=205.21,222.21
XS Rating Curve= 0 ,0
Exp/Cntr(USF)=0,0
Exp/Cntr=0.3,0.1

Type RM Length L Ch R = 1 ,4201    ,304.3,300.6,297.1
XS GIS Cut Line= 6
1606886.30479626495128.6944235121606956.78890726495180.725815505
1607014.83603525495228.2181745921607092.93233576495290.685897425
1607157.48896517495330.1736793371607234.67713101495373.233632594
#Sta/Elev= 30
       0     766    11.4  760.41    32.5  752.34    81.5   741.5    95.8  733.19
   106.7  728.73   119.4   719.8   123.6  716.31   132.1  707.18   144.8   696.7
   161.8  680.69   165.5  678.09   178.6  675.09   191.8  675.67   195.4   674.4
  201.85 669.729   207.8  668.71  220.26669.7306   224.8  670.99   228.6  673.19
   245.1     686   273.4  703.21   297.2  719.11   304.9  723.29   309.2  724.56
     328  724.46   345.1  728.83   393.3  731.69   407.1  734.55   426.7  742.82
#Mann= 4 ,-1,0
       0      .1       0  137.61     .06       0  201.85    .045       0
  220.26      .1       0
Bank Sta=201.85,220.26
XS Rating Curve= 0 ,0
Exp/Cntr(USF)=0,0
Exp/Cntr=0.3,0.1

Type RM Length L Ch R = 1 ,3900    ,338.2,348.2,355.6
XS GIS Cut Line= 6
1606746.94713534495481.8521817621606831.20680934495505.443998083
1606903.42910583495525.6660705061606999.72550118495552.628615007
1607070.97601484495576.322465256 1607155.4784705495601.582913429
#Sta/Elev= 30
       0  777.16     8.4  770.85      22  762.71    39.1  757.18    60.4  751.68
    65.8  748.21    93.5  725.69   144.7  692.66   178.7  675.52   192.4  673.64
   203.2   663.7     206   662.3   209.4  662.07  219.81663.7024     223  665.03
   236.6  667.54     240   669.5   257.1  682.76   277.7  696.65   281.2  698.36
   284.7  698.89     295  698.04   298.5  698.64   301.9  700.32   330.2  720.47
   357.1  737.87   360.5  738.79   398.2  739.06   408.4  747.36   425.8  757.68
#Mann= 5 ,-1,0
       0      .1       0      60     .06       0   203.2    .045       0
  219.81     .06       0   282.5      .1       0
Bank Sta=203.2,219.81
XS Rating Curve= 0 ,0
Exp/Cntr(USF)=0,0
Exp/Cntr=0.3,0.1

Type RM Length L Ch R = 1 ,3552    ,257.1,251.8,245.1
XS GIS Cut Line= 2
1606709.83950097495554.3897814891606817.40093128495972.815565343
#Sta/Elev= 30
       0  770.95    10.6  764.53    37.5  757.39    45.6  752.81    48.3  750.33
      59   737.1    71.6   725.7    81.8  709.91    98.7  691.43   125.8  666.68
   128.7  664.94   132.6   663.8   146.1   662.5   186.8  662.71   190.2  661.27
  195.35 657.295   196.9  656.51   203.7  656.21  211.91657.2924   230.8  659.14
   243.3  664.46   254.5  666.23   308.7  666.26   329.1  667.38   342.6  672.78
   365.9   678.1   383.3  683.97   393.4  688.27   417.1  696.36     432  703.33
#Mann= 5 ,-1,0
       0      .1       0      20     .06       0     120     .07       0
  195.35    .045       0  211.91      .1       0
Bank Sta=195.35,211.91
XS Rating Curve= 0 ,0
Exp/Cntr(USF)=0,0
Exp/Cntr=0.3,0.1

Type RM Length L Ch R = 1 ,3300    ,292.7,299.9,303.1
XS GIS Cut Line= 6
1606395.98294225495777.4985720961606465.87945601495830.136590168
1606525.79042542495875.2546101661606605.67215542495935.412298262
1606665.58345293 495980.530318261606735.47996667496033.168008253
#Sta/Elev= 30
       0  710.92     6.2  708.34    22.5  699.04    42.8   690.2    59.9  684.32
    75.7  674.83   116.8  654.24   125.5  653.25   151.3  653.65     156  655.45
   167.7  662.79   174.3  663.84   193.4  663.34   195.8  662.03   202.9  653.53
   207.1   651.5   209.8  651.27  222.56653.5262   244.1  658.14   256.7  655.05
   272.8  661.08   281.1  660.58   284.8  661.28   297.5  667.46   329.3   676.2
   366.1  688.46   385.5  693.72   400.2   699.3   416.6  707.37     425  712.51
#Mann= 5 ,-1,0
       0      .1       0      60     .06       0   202.9    .045       0
  222.56     .06       0   312.5      .1       0
#XS Ineff= 2 , 0
          171.28  677.09   245.9          673.36
Permanent Ineff=
       F       F
Bank Sta=202.9,222.56
XS Rating Curve= 0 ,0
Exp/Cntr(USF)=0,0
Exp/Cntr=0.3,0.1

Type RM Length L Ch R = 1 ,3000    ,147,138.9,133.6
XS GIS Cut Line= 6
1606266.20793934495958.6002440011606318.25671975496029.819589749
1606356.39771959496094.4375707511606405.28049584496181.675585255
1606442.91657542496246.5537363441606502.55490759496312.707147345
#Sta/Elev= 30
       0   669.4    11.1  670.25    22.2  669.61    56.6  662.46    77.8  661.28
   103.4  656.37   117.8  656.41   127.7   655.1     160  655.47     169  654.01
   182.6  655.12  196.48649.9547   213.6  648.91  221.26 649.956   230.8  657.53
   244.2  665.58   263.2  674.73   285.8  683.19   297.2  688.46   314.9  698.85
   331.7  711.33     339  715.75   347.8  722.99   365.5  739.14   378.4  754.31
   383.1  758.65     392   765.1   406.3  772.83   415.6  781.48   427.3  790.16
#Mann= 6 ,-1,0
       0     .06       0      80     .07       0  193.25     .06       0
  196.48    .045       0  221.26     .06       0  283.25      .1       0
Bank Sta=196.48,221.26
XS Rating Curve= 0 ,0
Exp/Cntr(USF)=0,0
Exp/Cntr=0.3,0.1

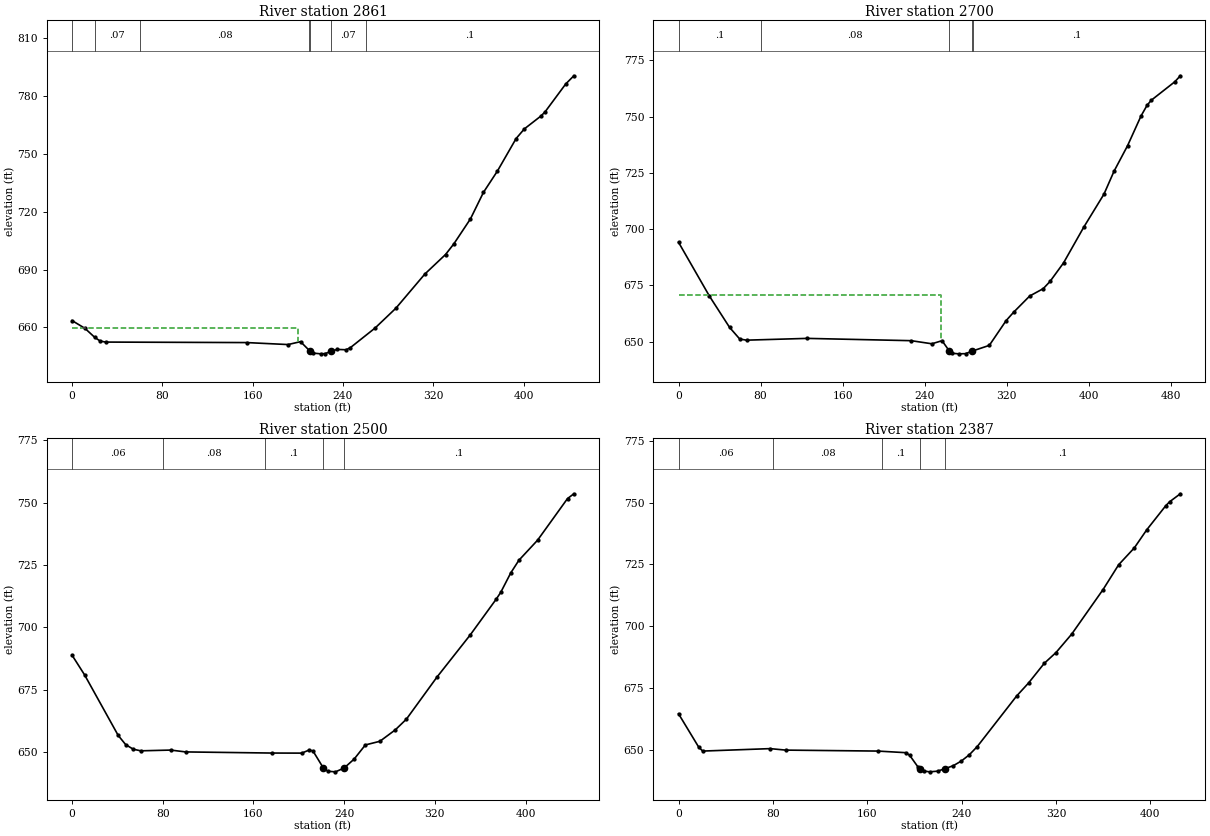
Type RM Length L Ch R = 1 ,2861    ,165.4,161.2,157.5
XS GIS Cut Line= 2
1606095.20275633 496141.840670121606492.35265287496341.597612129
#Sta/Elev= 30
       0  663.55    11.4  659.53      20   654.9    24.9  652.93    29.8  652.41
   154.7  652.15   191.4  651.12   202.4  652.63  210.88647.6691   213.4   646.7
   220.4  646.31   224.4  646.45  229.61647.6689     235   648.6   242.8  648.43
   246.5  649.48   268.5   659.7   286.9  669.96   312.6   687.7   330.9  697.81
   338.3  703.36     353   716.3   364.5  730.03   376.8  741.01   393.4  757.91
   400.7  762.92   415.4   769.6   419.1  771.78   437.4  786.24   444.6  790.48
#Mann= 7 ,-1,0
       0      .1       0      20     .07       0      60     .08       0
     210     .07       0  210.88    .045       0  229.61     .07       0
     260      .1       0
#XS Ineff= 2 , 0
          200.19  659.62
Permanent Ineff=
       F       F
Bank Sta=210.88,229.61
XS Rating Curve= 0 ,0
Exp/Cntr(USF)=0,0
Exp/Cntr=0.3,0.1

Type RM Length L Ch R = 1 ,2700    ,198.8,199.6,199.6
XS GIS Cut Line= 6
1605980.19626944496379.1262882571606131.81450734496388.157783836
1606206.61357035496393.6479303391606306.34532626496400.968125671
1606381.14406118496406.4582721741606468.40930659496412.863115013
#Sta/Elev= 30
       0  694.17    30.1  670.27    49.8  656.32    59.7  651.16    66.3  650.66
   125.4  651.45   226.9  650.43   247.1  649.05     257  650.43  264.22645.7575
   266.9  644.83   273.4  644.58     280  644.66  286.13645.7589   303.1  648.34
   319.5  659.35   326.9  663.12   342.5  670.29   355.7  673.56   362.3  676.75
   375.5  685.01   395.2  700.88   414.9  715.55   424.8  725.82   437.9  737.08
   451.1  750.36     457   755.1     461   757.3     484  765.53   489.4   768.2
#Mann= 5 ,-1,0
       0      .1       0      80     .08       0  264.22    .045       0
  286.13     .08       0  286.89      .1       0
#XS Ineff= 2 , 0
          256.36  670.56
Permanent Ineff=
       F       F
Bank Sta=264.22,286.13
XS Rating Curve= 0 ,0
Exp/Cntr(USF)=0,0
Exp/Cntr=0.3,0.1

Type RM Length L Ch R = 1 ,2500    ,117.5,113.8,110.7
XS GIS Cut Line= 3
1606012.46319455496579.1783538091606062.10693162496573.268385111
1606452.16486572496618.184147219
#Sta/Elev= 30
       0  688.85      11     681    40.7   656.7    47.3  653.02      54  651.18
    60.6  650.54      87  650.84   100.2   650.1   176.1  649.65   202.6  649.62
   209.2  650.88   212.5  650.47   221.7643.6266   225.7  642.35   232.3  642.12
  239.88643.6259   248.8  647.23   258.7   652.9   271.5  654.36   285.1  658.94
   294.9  663.23   321.8  680.05   351.2  696.98   374.3  711.43   378.1  714.03
   386.9  721.79   394.1  726.88   410.6  734.94     437  751.61   442.6  753.53
#Mann= 5 ,-1,0
       0     .06       0   79.99     .08       0  169.99      .1       0
   221.7    .045       0  239.88      .1       0
Bank Sta=221.7,239.88
XS Rating Curve= 0 ,0
Exp/Cntr(USF)=0,0
Exp/Cntr=0.3,0.1

Type RM Length L Ch R = 1 ,2387    ,106.4,108.4,110.6
XS GIS Cut Line= 6
  1606039.571163496757.4952883931606124.57591425496736.748282647
  1606197.436989496718.9641974781606294.81245041496696.182746983
1606368.75291933496682.821881315 1606455.6785985 496669.94526664
#Sta/Elev= 30
       0  664.57    17.1  651.09    20.5  649.49    77.7  650.48    90.9  649.88
   169.1  649.49   192.7  648.84     196  647.77   202.8  643.22  204.66642.4027
   208.3   641.4   212.9  641.09   219.6  641.36  226.16642.4005   233.1  643.61
   239.8  645.46   246.5  647.96   253.3  651.31   286.7  671.77   296.8  677.03
   310.1  684.97   320.1  689.36   333.4  696.81     360  714.84   373.2  724.86
   386.5  731.69     397  738.98     413  748.65   416.4  750.33   425.5  753.57
#Mann= 5 ,-1,0
       0     .06       0      80     .08       0   172.5      .1       0
  204.66    .045       0  226.16      .1       0
Bank Sta=204.66,226.16
XS Rating Curve= 0 ,0
Exp/Cntr(USF)=0,0
Exp/Cntr=0.3,0.1