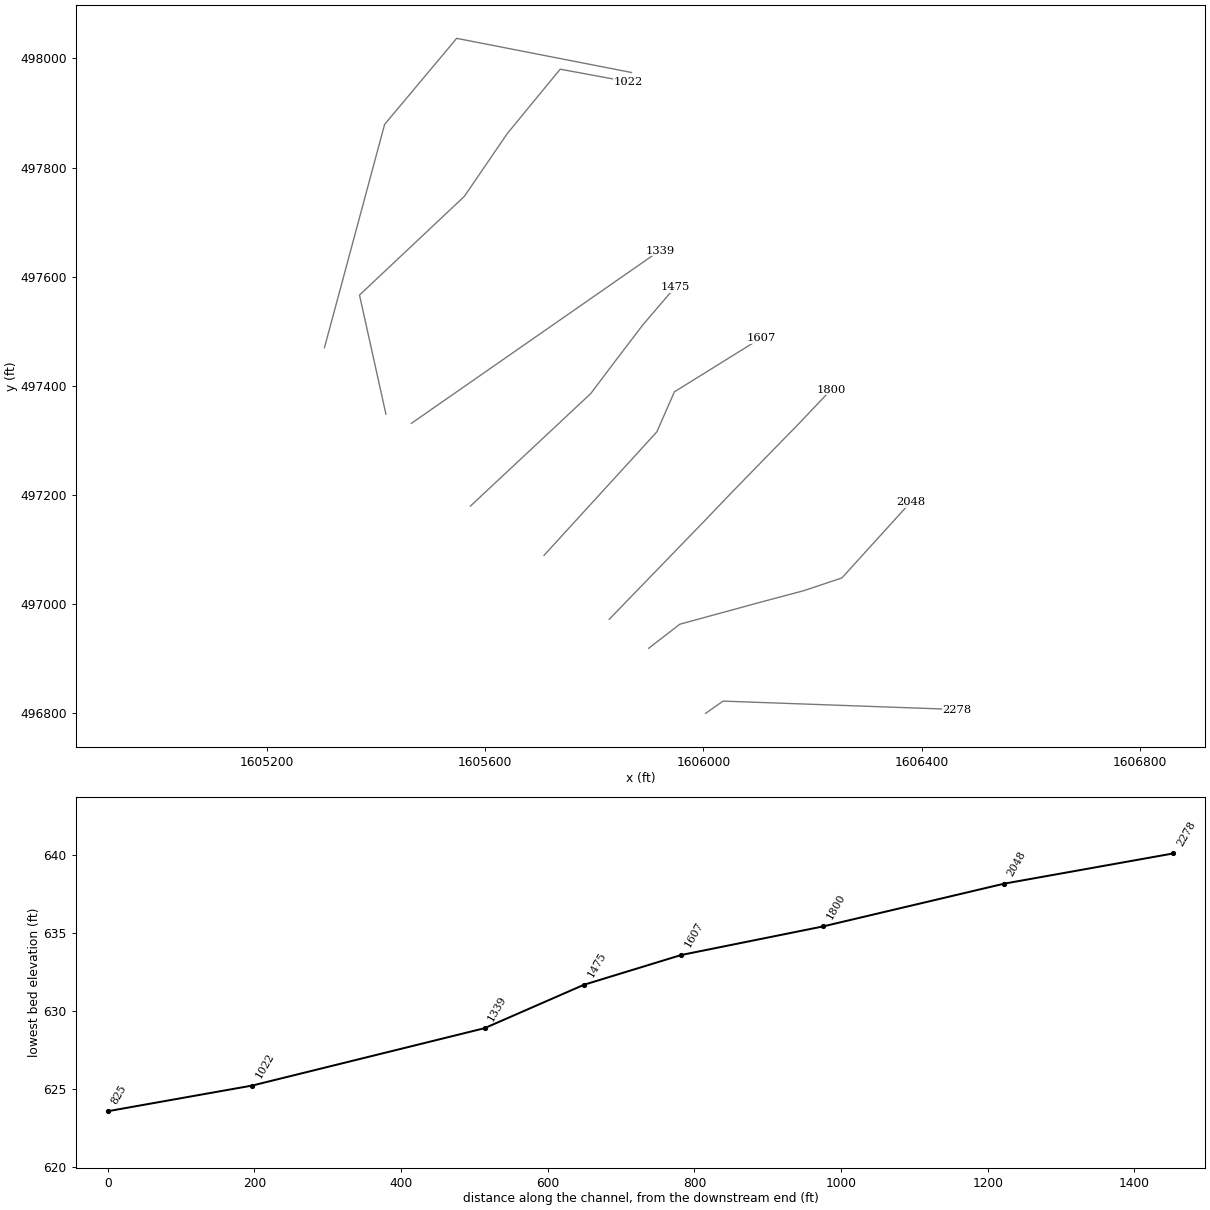
HEC-RAS study HogRn.prj: HogRn

--- HogRn.g01 (geometry) --- (continued)

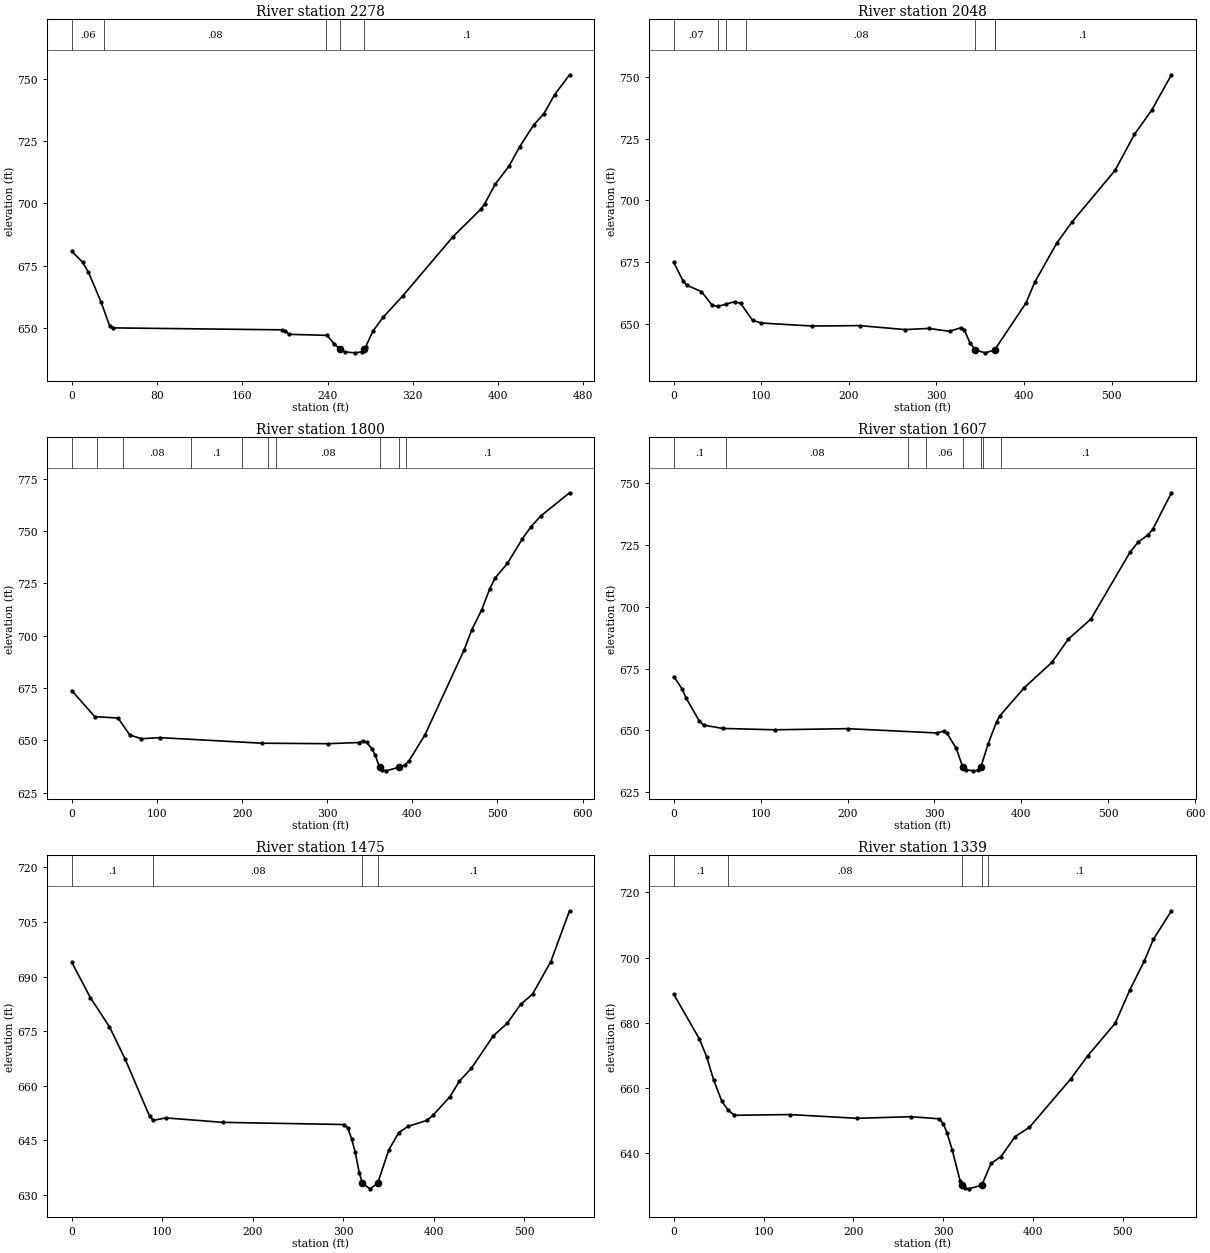
Type RM Length L Ch R = 1 ,2278    ,226.6,230.6,234.3
XS GIS Cut Line= 3
1606004.18923837496800.2111831331606036.10306934496822.669064187
1606463.98480311496807.303145571
#Sta/Elev= 30
       0  680.79      10  676.46    15.5  672.51    27.5  660.43    35.5  650.89
    38.3  650.13     197  649.35   200.3  648.98   203.6  647.56   239.7  647.13
   246.3  643.62  251.98641.5643   256.1   640.5     266  640.13   272.5  640.57
  274.23641.5648   275.8  642.47   282.4   648.7   292.2  654.38   310.4  662.84
   357.9  686.72   384.1  697.78   387.4  699.72   397.3  707.62   410.4  714.95
   420.3  722.67   433.4  731.35   443.2  736.03   453.1  743.49   467.2  751.55
#Mann= 5 ,-1,0
       0     .06       0      30     .08       0  239.02      .1       0
  251.98    .045       0  274.23      .1       0
Bank Sta=251.98,274.23
XS Rating Curve= 0 ,0
Exp/Cntr(USF)=0,0
Exp/Cntr=0.3,0.1

Type RM Length L Ch R = 1 ,2048    ,242.6,247.5,253
XS GIS Cut Line= 6
1605899.98888999496919.4715587271605956.96287109496963.549585254
1606110.99685815497005.5174036221606183.57151614497024.801813875
1606253.79527239497048.2719288891606379.89289745497187.208378165
#Sta/Elev= 30
       0  674.86    10.8  667.19      15  665.58    31.6  663.03    43.7  657.56
    50.7  657.02      60  658.01    69.4   658.9    76.3  658.29    89.9  651.38
   100.1  650.28   157.9  649.06   212.3  649.23   264.2  647.62     291  648.08
   314.9  646.92   328.1  648.39   331.6  647.61   338.5  642.09  344.54639.3258
   355.8  638.19  366.32639.3253   402.1  658.33   412.3  666.86   437.5  682.74
   455.2  691.43     504  712.19   526.1  726.78   545.7  736.52   568.4  750.94
#Mann= 7 ,-1,0
       0     .07       0      50     .08       0      60     .07       0
   82.03     .08       0  344.54    .045       0  366.32     .08       0
  366.78      .1       0
Bank Sta=344.54,366.32
XS Rating Curve= 0 ,0
Exp/Cntr(USF)=0,0
Exp/Cntr=0.3,0.1

Type RM Length L Ch R = 1 ,1800    ,188.6,193,196.2
XS GIS Cut Line= 6
1605827.60537876 496972.503947171605999.60873501497150.110328168
1606051.47510108497204.2906659991606121.27942343497275.896165833
1606173.69926609497329.5354942531606233.95866001497392.977624595
#Sta/Elev= 30
       0  673.74    26.8  661.35    54.3  660.66      68   652.6    81.7  650.79
   103.4   651.3   223.3  648.64   300.6  648.41   337.1  648.96   342.4  649.78
   346.3  649.03   352.5  646.02   356.3  643.05  361.56637.0723   364.6  635.79
   369.2  635.44  383.78637.0707   391.1  638.17   395.8  640.03     415  652.74
   460.9  693.24     470  702.94   481.6  712.41   490.9  722.36   497.2  727.49
   511.8  734.58   529.2  746.24   539.6  752.11   551.2   757.3   584.7  768.26
#Mann= 10 ,-1,0
       0      .1       0      30     .07       0      60     .08       0
     140      .1       0     200     .08       0     230      .1       0
     240     .08       0  361.56    .045       0  383.78     .08       0
  392.25      .1       0
Bank Sta=361.56,383.78
XS Rating Curve= 0 ,0
Exp/Cntr(USF)=0,0
Exp/Cntr=0.3,0.1

Type RM Length L Ch R = 1 ,1607    ,134.9,132.6,130.9
XS GIS Cut Line= 4
 1605708.2946867497089.6949126721605914.88950977 497315.83248928
1605946.99546201497389.1178150321606105.43135673497487.529538185
#Sta/Elev= 30
       0  671.78     9.7  666.65    14.4  662.93    29.4  653.74    34.3  652.13
    56.2  650.77   116.3  650.22   200.2  650.68   302.9  648.93   310.8   649.7
   314.6  648.74   325.1  642.68   332.2  635.54  333.42635.0328   335.8  634.07
   344.4  633.61   350.2  633.83   353.3635.0135   361.9  644.66   371.6   653.5
   375.2  655.86   403.4  667.26   435.5  677.61   454.1  686.92   480.1  695.03
   524.9  721.96   534.5   726.2   545.8  729.06   551.2  731.31   572.8  746.12
#Mann= 8 ,-1,0
       0      .1       0      60     .08       0     270     .07       0
     290     .06       0  333.42    .045       0   353.3     .07       0
   356.3     .06       0   376.3      .1       0
Bank Sta=333.42,353.3
XS Rating Curve= 0 ,0
Exp/Cntr(USF)=0,0
Exp/Cntr=0.3,0.1

Type RM Length L Ch R = 1 ,1475    ,138.3,135.7,133.6
XS GIS Cut Line= 5
1605573.51524928497179.9764312551605793.84055491497386.019923036
1605842.00854704497449.900160158 1605889.1331247497511.680220316
 1605948.2629277 497580.86774599
#Sta/Elev= 30
       0   693.9    20.4  684.27    41.6  676.22      59  667.31    85.9  651.68
      90   650.5   103.9  651.19   166.8  649.97   301.2  649.37   305.2  648.38
   309.3  645.53   313.4  641.74   317.8  636.18  321.34 633.215   329.8   631.7
   338.2633.2272   350.4  642.34   361.4   647.1   371.5  648.84   392.6  650.49
   399.4  651.91   418.3  657.06   428.6  661.32   441.7  664.77     466  673.71
   481.4  677.17   496.3  682.36   509.5   685.2   529.7  694.15   550.4   708.1
#Mann= 4 ,-1,0
       0      .1       0      90     .08       0  321.34    .045       0
   338.2      .1       0
Bank Sta=321.34,338.2
XS Rating Curve= 0 ,0
Exp/Cntr(USF)=0,0
Exp/Cntr=0.3,0.1

Type RM Length L Ch R = 1 ,1339    ,307.1,316.6,324.5
XS GIS Cut Line= 2
1605465.19749486497331.3817603391605920.33367062497647.937144888
#Sta/Elev= 30
       0  688.69    28.5  674.98    36.5  669.56    44.5   662.3    53.4  655.93
    60.4  653.13    67.5  651.52   129.3  651.74   204.4  650.59   264.3  651.08
   295.9  650.42   300.3  648.84   304.3  646.19   310.3  640.73   318.9  631.39
  321.47630.0155   324.4  629.02   328.3  628.91  343.07 630.014   353.4  636.71
   364.5  638.84   380.2  644.95   396.2  647.83   442.3  662.72   461.1  669.79
   491.8  679.83   508.1   690.1   524.1   698.9   534.2  705.57   554.4  714.37
#Mann= 5 ,-1,0
       0      .1       0      60     .08       0  321.47    .045       0
  343.07     .06       0     350      .1       0
Bank Sta=321.47,343.07
XS Rating Curve= 0 ,0
Exp/Cntr(USF)=0,0
Exp/Cntr=0.3,0.1

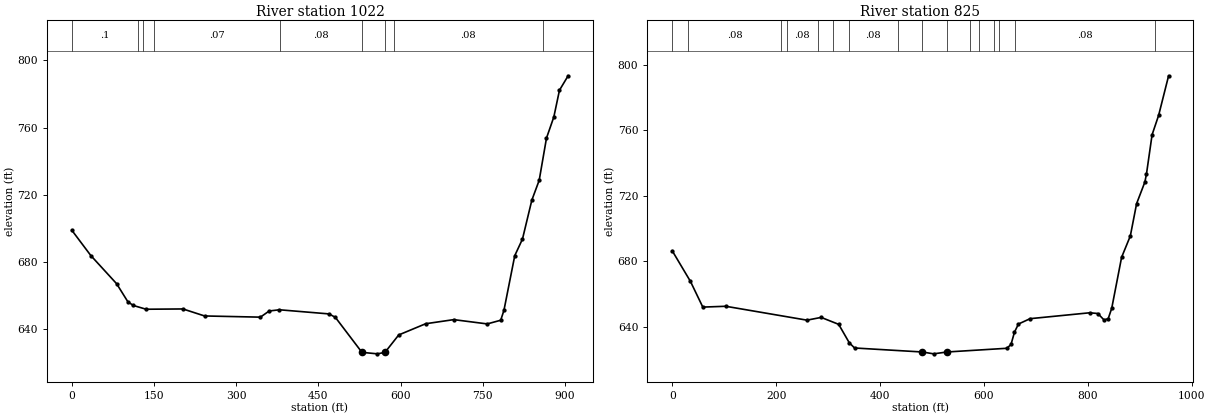
Type RM Length L Ch R = 1 ,1022    ,198.3,197.3,194.4
XS GIS Cut Line= 6
1605418.62462041497348.3352181581605370.23758517497566.387347354
1605562.32742068497747.2095891981605640.97084755497862.303807986
1605737.81827594 497980.111906241605862.03577637 497957.18313133
#Sta/Elev= 30
       0  698.85    34.7  683.77    81.8  666.98   102.2  656.29     112  654.06
   135.6  651.79   202.8  651.96   242.2  647.79   344.1  647.08   360.2  650.75
   378.8  651.47   469.3  649.01   480.9  646.96  529.39626.1133   557.7  625.23
  571.44626.1123   596.5  636.48   645.7  643.16   696.9   645.6     758  643.05
   782.6  645.24   788.5  651.17   808.2  683.68   822.3   693.6   839.4  716.78
   852.8  728.58   866.1  753.71   879.5  766.29   889.8  782.23   905.6  790.82
#Mann= 9 ,-1,0
       0      .1       0     120     .07       0     130      .1       0
     150     .07       0  380.75     .08       0  529.39    .045       0
  571.44     .07       0  587.18     .08       0  859.24      .1       0
Bank Sta=529.39,571.44
XS Rating Curve= 0 ,0
Exp/Cntr(USF)=0,0
Exp/Cntr=0.3,0.1

Type RM Length L Ch R = 1 ,825     ,,,
XS GIS Cut Line= 5
1605306.03046045497469.8285207721605416.23555812497878.998057285
1605523.02295573498006.4892628441605548.16994407 498036.64283292
1605868.42110623497974.105447792
#Sta/Elev= 30
       0   686.4      35  667.76    58.8  652.09     103  652.59   259.3  644.12
   286.7   645.8   320.4  641.57   340.8  630.33     351  627.15  481.46624.7074
   503.3  623.58  528.79624.7076   644.2  626.97   652.2  629.31   658.9  636.85
   666.5  641.76   688.9  645.03   803.6  648.62   819.4  648.18   831.5  644.16
   839.4  645.12   846.1  651.36   865.1  682.45   881.9  695.48     894  715.21
   909.9  728.36     913  733.28   923.8  757.21   936.4  769.05   955.6  793.18
#Mann= 16 ,-1,0
       0     .06       0      30     .08       0     210     .07       0
     220     .08       0     280     .07       0     310    .025       0
     340     .08       0  433.75     .07       0  481.46    .045       0
  528.79     .07       0  573.75     .08       0  590.06     .07       0
  620.06     .08       0  629.32     .07       0  659.32     .08       0
  929.32      .1       0
Bank Sta=481.46,528.79
XS Rating Curve= 0 ,0
Exp/Cntr(USF)=0,0
Exp/Cntr=0.3,0.1
LCMann Table=0

Chan Stop Cuts=-1
Use User Specified Reach Order=0
Composite Channel Slope=5